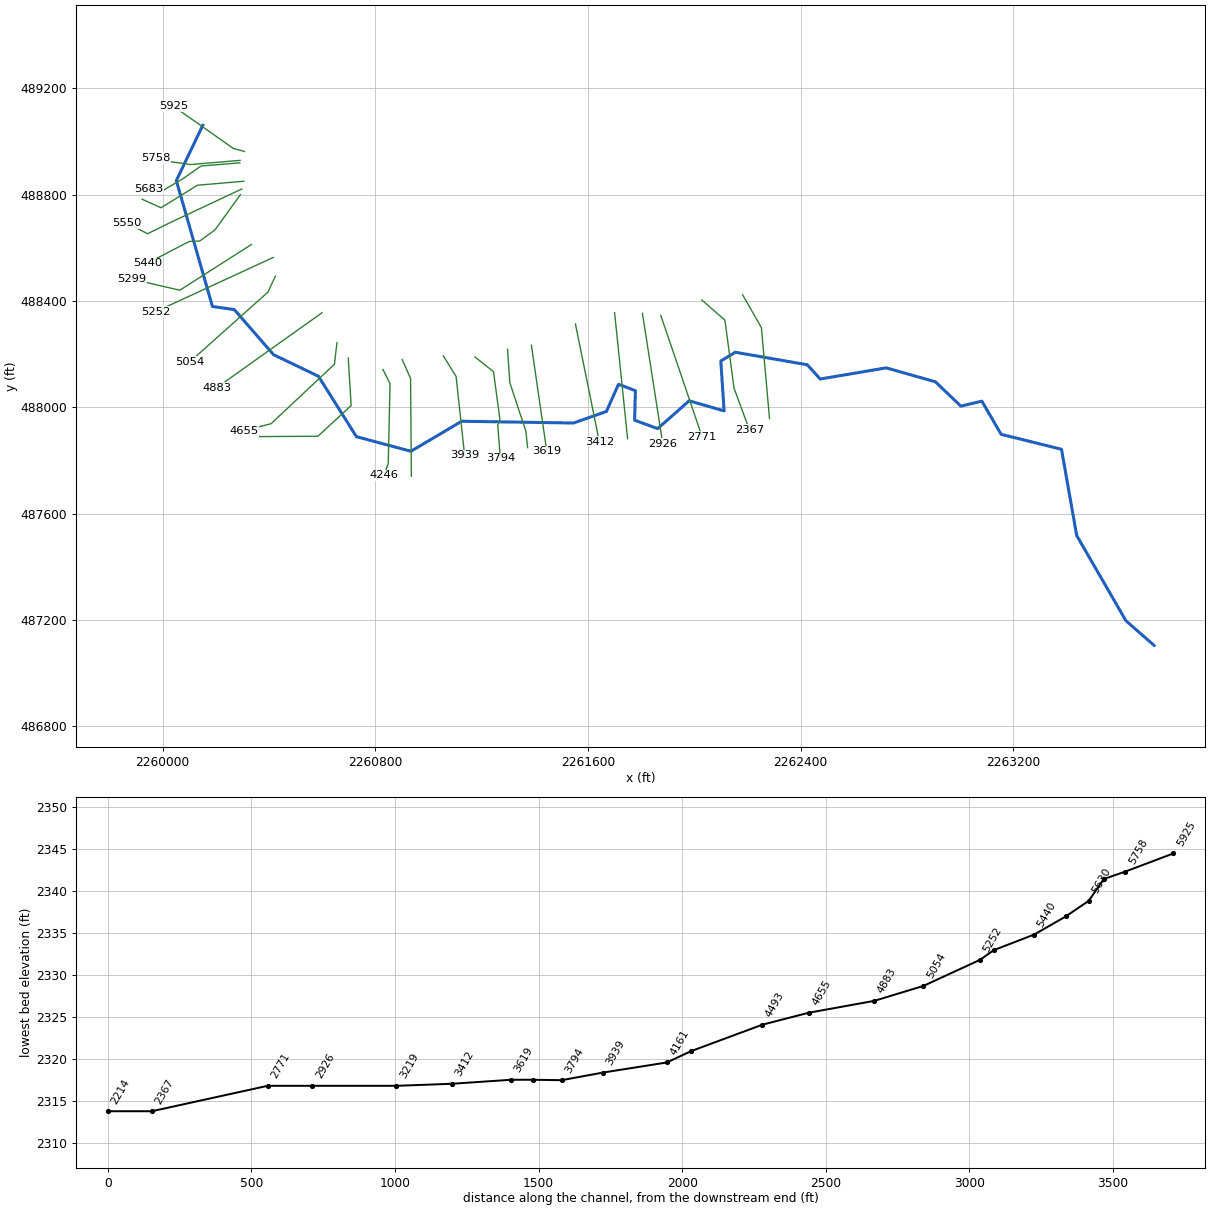
--- GLADERN.prj (project) ---

Proj Title=GLADERN
Current Plan=p01
Default Exp/Contr=0,0
English Units
Geom File=g01
Flow File=f01
Plan File=p01
Background Map Layer=Inundation Boundary (01pct Value_0)
Background Map Layer=Inundation Boundary (01pct Value_0)
Background Map Layer=Inundation Boundary (01pct Value_0)
BEGIN DESCRIPTION:
----------MODEL BY WOOD PLC 2021----------
Stream Name: Glade Run
Flood Zone: Enhanced Approximate
Pocahontas County, WV
HEC-RAS Version: RAS 6.1
Vertical Datum: NAVD88
Projection: NAD 1983 StatePlane West Virginia S FIPS 4702 (US Feet)
Terrain: 1-meter LIDAR (FEMA Region III 3DEP collected 2016-2018)
Land Use: 2019 NLCD
Hydrologic Method:
WV SIR2010-5033 regression equations
END DESCRIPTION:
DSS File=dss
DSS Export Rating Curves= 0
DSS Export Rating Curve Sorted= 0
DSS Export Volume Flow Curves= 0
DXF OffsetX= 0
DXF OffsetY= 0
DXF ScaleX= 0
DXF ScaleY= 0

--- GLADERN.p01 (plan) ---

Plan Title=Floodplain
Program Version=6.10
Short Identifier=Floodplain
Geom File=g01
Flow File=f01
Subcritical Flow
K Sum by GR= 0
Std Step Tol= 0.01
Critical Tol= 0.01
Num of Std Step Trials= 20
Max Error Tol= 0.3
Flow Tol Ratio= 0.001
Split Flow NTrial= 30
Split Flow Tol= 0.02
Split Flow Ratio= 0.02
Log Output Level= 0
Friction Slope Method= 1
Unsteady Friction Slope Method= 2
Unsteady Bridges Friction Slope Method= 1
Parabolic Critical Depth
Global Vel Dist= 0 , 0 , 0
Global Log Level= 0
CheckData=True
Encroach Param=-1 ,0,0, 0
Computation Interval=0.1SEC
Output Interval=1SEC
Instantaneous Interval=Max Profile
Mapping Interval=1HOUR
Computation Time Step Use Courant=        0
Computation Time Step Use Time Series=    0
Computation Time Step Count To Double=0
Computation Time Step Max Doubling=0
Computation Time Step Max Halving=0
Computation Time Step Residence Courant=0
Run HTab= 0
Run UNet= 0
Run Sediment= 0
Run PostProcess= 0
Run WQNet= 0
Run RASMapper=-1
UNET Theta= 0
UNET Theta Warmup= 0
UNET ZTol= 0
UNET ZSATol= 0
UNET MxIter= 0
UNET Max Iter WO Improvement= 0
UNET MaxInSteps= 0
UNET DtIC= 0
UNET DtMin= 0
UNET MaxCRTS= 0
UNET WFStab= 0
UNET SFStab= 0
UNET WFX= 1
UNET SFX= 1
UNET Gravity=32.174
UNET 1D Methodology=Finite Difference
UNET DSS MLevel= 1
UNET Pardiso=0
UNET DZMax Abort= 0
UNET Use Existing IB Tables= 0
UNET Froude Reduction=False
UNET Froude Limit= 0
UNET Froude Power= 0
UNET D1 Cores= 0
UNET WindReference=Eulerian
UNET WindDragFormulation=Hsu (1988)
UNET D2 Coriolis=0
UNET D2 Cores= 0
UNET D2 Theta= 1
UNET D2 Theta Warmup= 1
UNET D2 Z Tol= 0.01
UNET D2 Volume Tol= 0.01
UNET D2 Max Iterations= 20
UNET D2 Equation= 0
UNET D2 RampUpFraction=0.1
UNET D2 TimeSlices= 1
UNET D2 Turbulence Formulation=Non-Conservative (original)
UNET D2 Eddy Viscosity=0.3
UNET D2 Transverse Eddy Viscosity=0.1
UNET D2 Smagorinsky Mixing=0
UNET D2 BCVolumeCheck=0
UNET D2 Cores=0
UNET D2 SolverType=PARDISO (Direct)
UNET D2 Minimum Iterations= 2147483647
UNET D2 Maximum Iterations= 2147483647
UNET D2 Restart Number= 10
UNET D2 Relaxation Coeff=1.3
UNET D2 SOR Precondition Iterations= 10
UNET D2 ILUT Maximum Fill= 8
UNET D2 ILUT Tolerance=1E-08
UNET D1D2 MaxIter= 0
UNET D1D2 ZTol=0.01
UNET D1D2 QTol=0.1
UNET D1D2 MinQTol=1
DSS File=dss
Write IC File= 0
Write IC File at Fixed DateTime=0
Write IC File at Sim End=0
Echo Input=False
Echo Parameters=False
Echo Output=False
Write Detailed= 0
HDF Write Warmup=0
HDF Write Time Slices=0
HDF Flush=0
HDF Compression= 1
HDF Chunk Size= 1
HDF Spatial Parts= 1
HDF Use Max Rows=0
HDF Fixed Rows= 1
Calibration Method= 0
Calibration Iterations= 20
Calibration Max Change=0.05
Calibration Tolerance=0.2
Calibration Maximum=1.5
Calibration Minimum=0.5
Calibration Optimization Method= 1
WQ AD Non Conservative
WQ ULTIMATE=-1
WQ Max Comp Step=1HOUR
WQ Output Interval=15MIN
WQ Output Selected Increments= 0
WQ Output face flow=0
WQ Output face velocity=0
WQ Output face area=0
WQ Output face dispersion=0
WQ Output cell volume=0
WQ Output cell surface area=0
WQ Output cell continuity=0
WQ Output cumulative cell continuity=0
WQ Output face conc=0
WQ Output face dconc_dx=0
WQ Output face courant=0
WQ Output face peclet=0
WQ Output face adv mass=0
WQ Output face disp mass=0
WQ Output cell mass=0
WQ Output cell source sink temp=0
WQ Output nsm pathways=0
WQ Output nsm derived pathways=0
WQ Create Restart=0
WQ Fixed Restart=0
WQ System Summary=0
WQ Write To DSS=0
Sorting and Armoring Iterations= 10
XS Update Threshold= 0.02
Bed Roughness Predictor= 0
Hydraulics Update Threshold= 0.02
Energy Slope Method= 1
Volume Change Method= 1
Sediment Retention Method= 0
Sediment TS Multiplier= 1
Warm Up Method= 0
XS Weighting Method= 0
Number of US Weighted Cross Sections= 1
Number of DS Weighted Cross Sections= 1
Upstream XS Weight=0
Main XS Weight=1
Downstream XS Weight=0
Number of DS XS's Weighted with US Boundary= 1
Upstream Boundary Weight= 1
Weight of XSs Associated with US Boundary= 0
Number of US XS's Weighted with DS Boundary= 1
Downstream Boundary Weight= 0.5
Weight of XSs Associated with DS Boundary= 0.5
Percentile Method= 0
Sediment Output Level= 3
Mass or Volume Output= 0
Output Increment Type= 1
Profile and TS Output Increment= 1
Transport Output Increment 1
XS Output Flag= 0
XS Output Increment= 10
Read HDF5 Sediment Hotstart= 0
Sediment Hotstart Type= 0
Write Gradation File= 0
Read Gradation Hotstart= 0
Write HDF5 File= 1
Write Binary Output= 1
Write DSS Sediment File= 0
DSS Sediment Output Type= 1
SV Curve= 0
Specific Gage Flag= 0
Subcell Erosion Methods= 0
Subcell Deposition Methods= 0
Advection Scheme= 1
Matrix Solver= 0
Implicit Weighting Factor= 1
Maximum Outer Loop Convergence Iterations= 5
Convergence Maximum Absolute= 0.001
Convergence RMSE= 0.0001
Grain Fractions Max Abs Error= 0.001
Max Subgrid Regions= 1
Max Subgrid Length Scale= 3.402823E+38
Initial Layer Thickness= 3.402823E+38
Min Layer Thickness= 3.402823E+38
Max Layer Thickness= 3.402823E+38
Number of Layers= 5

--- GLADERN.f01 (steady flow) ---

Flow Title=Flow
Program Version=6.10
Number of Profiles= 6
Profile Names=01pct,10pct,04pct,02pct,0_2pct,01plus
River Rch & RM=GLADERN,Main            ,5925
     541     285     380     458     756     800
River Rch & RM=GLADERN,Main            ,3939
     602     319     424     510     840     891
Boundary for River Rch & Prof#=GLADERN,Main            , 1
Up Type= 0
Dn Type= 3
Dn Slope=0.04598
Boundary for River Rch & Prof#=GLADERN,Main            , 2
Up Type= 0
Dn Type= 3
Dn Slope=0.04598
Boundary for River Rch & Prof#=GLADERN,Main            , 3
Up Type= 0
Dn Type= 3
Dn Slope=0.04598
Boundary for River Rch & Prof#=GLADERN,Main            , 4
Up Type= 0
Dn Type= 3
Dn Slope=0.04598
Boundary for River Rch & Prof#=GLADERN,Main            , 5
Up Type= 0
Dn Type= 3
Dn Slope=0.04598
Boundary for River Rch & Prof#=GLADERN,Main            , 6
Up Type= 0
Dn Type= 3
Dn Slope=0.04598
DSS Import GetInterval= 0
DSS Import GetPeak= 0
DSS Import FillOption= 0

--- GLADERN.g01 (geometry) ---

Geom Title=Geometry
Program Version=6.10

River Reach=GLADERN         ,Main
Reach XY= 30
     2260151.375       489061.08     2260051.797      488852.898
     2260187.708      488379.352     2260269.825      488367.661
     2260417.378      488198.085     2260586.522      488116.723
     2260729.291      487889.533     2260934.407      487834.612
     2261125.336      487947.528     2261546.116      487940.884
     2261669.917      487984.459     2261715.307      488086.603
     2261778.881      488062.647       2261775.9       487951.52
     2261862.716      487919.751     2261981.114      488024.458
     2262112.615      487986.435     2262100.206      488174.005
     2262154.709      488207.099     2262425.445      488160.027
     2262474.087      488106.382     2262722.336      488148.364
     2262907.654      488095.8882263003.19879738488004.367452897
     2263082.255      488023.145     2263154.736      487898.435
       2263381.9      487841.976      2263439.09       487517.53
     2263624.245      487196.997     2263730.173      487104.345

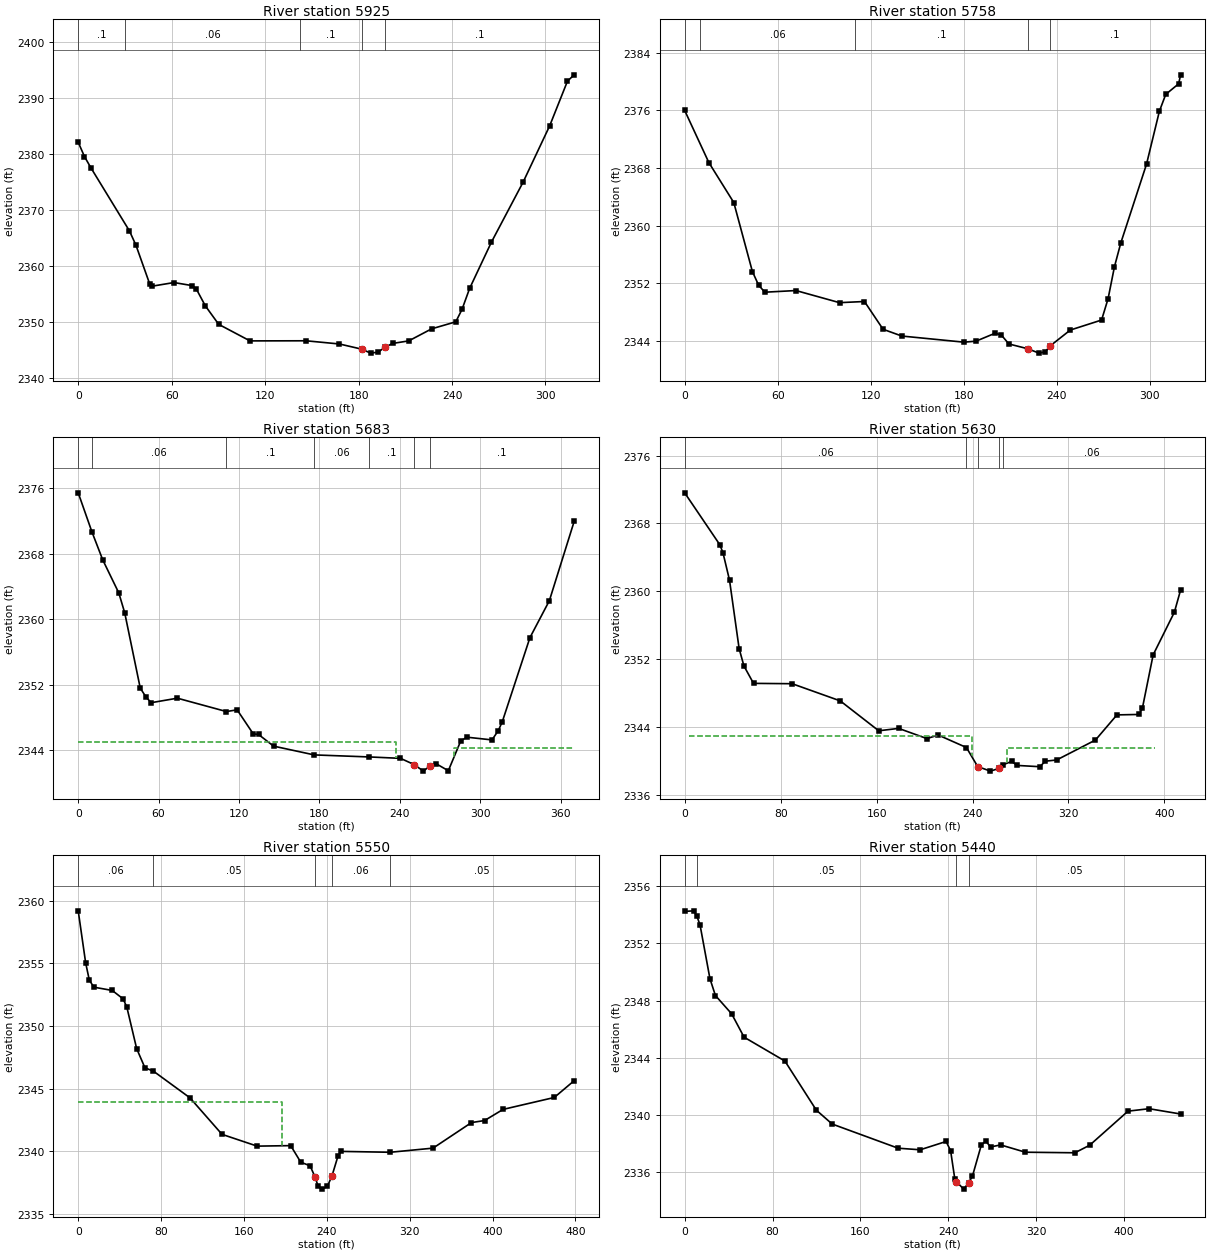
Type RM Length L Ch R = 1 ,5925    ,160.3,167.3,172.4
XS GIS Cut Line= 3
2260308.04476798488962.7018051562260266.86733812 488973.44609046
2260041.33569587489132.267477017
#Sta/Elev= 30
       0 2382.09       4 2379.54     8.1 2377.55    32.9 2366.28    37.1 2363.71
    45.8  2356.9    47.2 2356.42    61.5 2357.08      73 2356.54    75.9 2355.89
    81.6 2352.93    90.2 2349.63   110.3 2346.68   146.3  2346.7   167.7 2346.13
   182.22345.196   187.7  2344.5   192.6 2344.68     1972345.566   201.9 2346.23
   212.2 2346.68   226.9 2348.83   242.4 2350.08   246.4 2352.29   251.3 2356.04
   265.3 2364.29   285.6 2374.96   302.7 2385.02   314.1 2392.97   318.4  2394.1
#Mann= 5 ,-1,0
       0      .1       0      30     .06       0  142.56      .1       0
   182.2    .045       0     197      .1       0
Bank Sta=182.2,197
XS Rating Curve= 0 ,0
Exp/Cntr=0.3,0.1

Type RM Length L Ch R = 1 ,5758    ,68.3,75.1,82.1
XS GIS Cut Line= 4
2260291.73599066488929.0081751012260105.30745475488913.301741672
2260023.36084555488924.9108446412259974.87576845 488937.88572443
#Sta/Elev= 30
       0    2376    15.6 2368.77    31.7 2363.22    43.7 2353.65    47.7 2351.77
    51.7 2350.79    71.8 2351.02    99.9 2349.34     116  2349.5     128 2345.65
   140.1 2344.71   180.2 2343.86     188    2344   200.4 2345.11   204.4 2344.83
   209.2 2343.61   221.5 2342.94   228.6 2342.34   232.7 2342.52   235.6  2343.3
   248.8 2345.54     269 2346.93   273.2 2349.89   277.3 2354.32   281.4 2357.62
     298 2368.55   306.3 2375.89   310.4 2378.23   318.7 2379.69     320 2380.94
#Mann= 5 ,-1,0
       0      .1       0      10     .06       0     110      .1       0
   221.5    .045       0   235.6      .1       0
Bank Sta=221.5,235.6
XS Rating Curve= 0 ,0
Exp/Cntr(USF)=0,0
Exp/Cntr=0.5,0.3

Type RM Length L Ch R = 1 ,5683    ,52.3,52.6,55
XS GIS Cut Line= 5
2260290.37148352488919.6253216182260145.00973834488907.830461606
2260079.15087962 488861.789171882260001.50841643 488815.64869905
2259948.24312046 488821.79469474
#Sta/Elev= 30
       0 2375.41    10.2 2370.66    18.3 2367.23    30.3 2363.19    34.7 2360.77
    46.3 2351.58    50.4 2350.54    54.4  2349.8      74 2350.35   110.6 2348.72
   118.6 2348.93   130.6    2346   134.6 2345.92   145.8  2344.5   176.1 2343.43
   217.3 2343.18   240.5 2343.01250.59852342.257   257.6 2341.45262.56012342.095
   266.9 2342.37   276.2  2341.5   285.5 2345.15   290.1 2345.59   308.8 2345.26
   313.5  2346.4   316.5 2347.49   337.1 2357.74   351.6 2362.25   370.1 2371.92
#Mann= 7 ,-1,0
       0      .1       0    10.2     .06       0   110.6      .1       0
   176.1     .06       0   217.3      .1       0250.5985    .045       0
262.5601      .1       0
#XS Ineff= 2 , 0
          236.85    2345  280.62         2344.29
Permanent Ineff=
       F       F
Bank Sta=250.5985,262.5601
XS Rating Curve= 0 ,0
Exp/Cntr(USF)=0,0
Exp/Cntr=0.5,0.3

Type RM Length L Ch R = 1 ,5630    ,80,80,75.8
XS GIS Cut Line= 5
2260305.39375886488850.4760079572260131.25721432488835.452462938
2260032.23839488488773.9878128442259993.96891282488750.769893042
2259923.50941906488782.710950334
#Sta/Elev= 30
       0 2371.61    29.3  2365.5    31.9 2364.57    37.4 2361.32    45.4 2353.27
    49.4 2351.23    57.4 2349.18    89.6 2349.14   129.7 2347.12   161.8  2343.6
   178.4 2343.88     202 2342.68   211.4  2343.1   234.9 2341.63   244.3 2339.39
   254.9 2338.85262.08222339.167   265.8 2339.62   272.6 2339.99   277.3 2339.52
   296.1 2339.37   300.7 2340.02   310.1 2340.16   342.5 2342.51   360.4 2345.47
   378.6 2345.52   381.6 2346.24   390.6 2352.54   408.3 2357.56   413.5 2360.18
#Mann= 5 ,-1,0
       0     .06       0   234.9      .1       0   244.3    .045       0
262.0822      .1       0   265.8     .06       0
#XS Ineff= 2 ,-1
    3.25  239.25    2343  268.59  392.392341.624
Permanent Ineff=
       F       F
Bank Sta=244.3,262.0822
XS Rating Curve= 0 ,0
Exp/Cntr(USF)=0,0
Exp/Cntr=0.5,0.3

Type RM Length L Ch R = 1 ,5550    ,115.4,110.1,105.2
XS GIS Cut Line= 4
2260297.88198635 488821.111806332260025.31552385488693.284692439
2259943.62197099488652.8122562032259867.20374576488693.355355279
#Sta/Elev= 30
       0 2359.19     7.2 2355.03    10.7 2353.67    15.1  2353.1    32.8 2352.84
    43.3 2352.17    46.9 2351.52    56.4  2348.2    64.4 2346.67    72.6  2346.4
   107.9 2344.27   138.8 2341.36   172.7 2340.42   205.1 2340.46   214.8 2339.14
   223.8 2338.85   228.52337.977   231.6 2337.22   235.4 2336.99   240.5 2337.21
     245 2338.06   250.9 2339.67   253.9    2340   301.1 2339.93   342.5 2340.26
   379.6  2342.3   392.2 2342.46   410.1 2343.35   459.5  2344.3   478.7 2345.64
#Mann= 5 ,-1,0
       0     .06       0    72.6     .05       0   228.5    .045       0
     245     .06       0   301.1     .05       0
#XS Ineff= 2 , 0
          196.97 2343.98
Permanent Ineff=
       F       F
Bank Sta=228.5,245
XS Rating Curve= 0 ,0
Exp/Cntr(USF)=0,0
Exp/Cntr=0.3,0.1

Type RM Length L Ch R = 1 ,5440    ,133.7,140.8,147.3
XS GIS Cut Line= 5
2260292.98361896488799.8525980232260197.20638304488667.380034374
2260139.53724466488625.4497878122260100.81456498488624.167410365
2259942.69843906488542.083013669
#Sta/Elev= 30
       0 2354.24     8.2 2354.28    11.1 2353.91      14 2353.29      23 2349.54
      28 2348.36    42.8 2347.08    54.1 2345.45    91.3 2343.78   119.9 2340.35
   134.3 2339.38   194.4 2337.69   214.5 2337.58   238.1 2338.16   242.2 2337.52
   246.1 2335.51 247.4932335.357   254.1 2334.83   258.7 2335.28   262.1 2335.74
   270.2 2337.92   274.2 2338.18   278.7 2337.78   287.8 2337.92   310.3 2337.41
   355.4 2337.37   368.9  2337.9   403.8 2340.28     423 2340.45   451.7 2340.08
#Mann= 4 ,-1,0
       0     .06       0    11.1     .05       0 247.493    .045       0
   258.7     .05       0
Bank Sta=247.493,258.7
XS Rating Curve= 0 ,0
Exp/Cntr=0.3,0.1

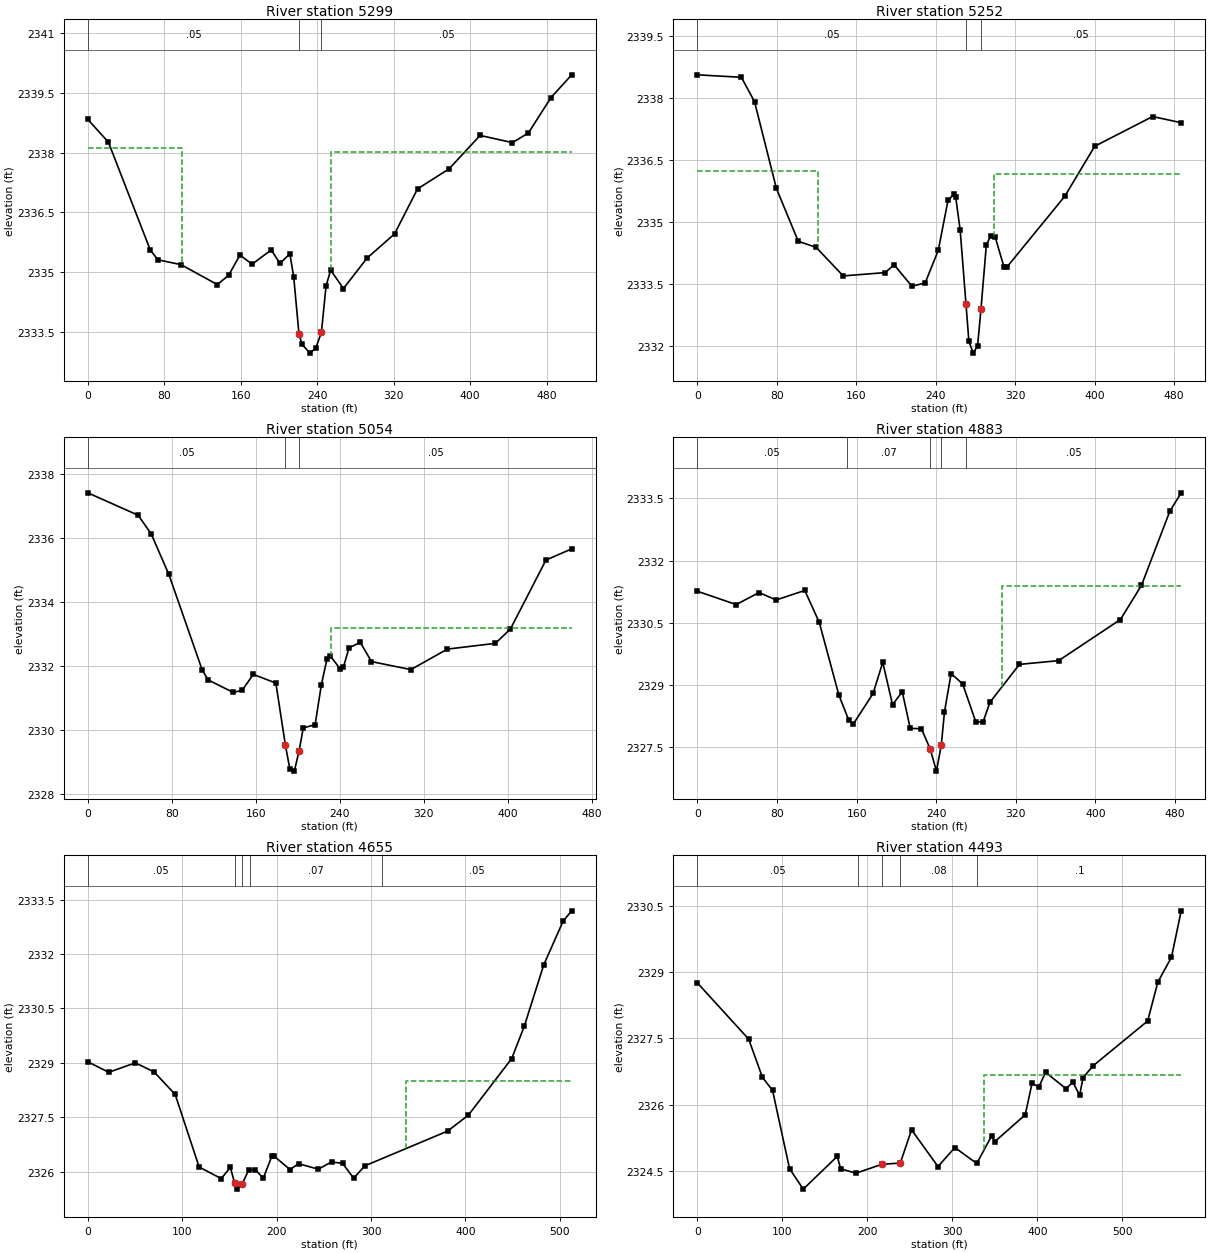
Type RM Length L Ch R = 1 ,5299    ,49.4,47.6,46
XS GIS Cut Line= 3
2260334.29193635488612.3625914922260064.79601996488440.455725607
2259883.13024902488482.494085823
#Sta/Elev= 30
       0 2338.83    21.5 2338.26    65.4 2335.55    73.4 2335.31    97.4 2335.19
   135.4 2334.69   147.2 2334.92   159.1 2335.43   171.8  2335.2   191.9 2335.56
   200.8 2335.22   211.3 2335.46   215.3 2334.89   220.8 2333.46     224 2333.19
   232.3 2332.97   238.5  2333.1   244.3 2333.49   249.2 2334.66     254 2335.05
   267.4 2334.59   291.9 2335.35   320.8 2335.96   344.9 2337.09   377.8 2337.59
   410.3 2338.43   444.1 2338.25   460.8 2338.49   484.5 2339.38   506.1 2339.95
#Mann= 3 ,-1,0
       0     .05       0   220.8    .045       0   244.3     .05       0
#XS Ineff= 2 , 0
           98.55 2338.11  254.11         2338.01
Permanent Ineff=
       F       F
Bank Sta=220.8,244.3
XS Rating Curve= 0 ,0
Exp/Cntr(USF)=0,0
Exp/Cntr=0.3,0.1

Type RM Length L Ch R = 1 ,5252    ,192.2,197.4,201.2
XS GIS Cut Line= 2
 2260416.3663694488563.7447443512259974.01371855488359.742110075
#Sta/Elev= 30
       0 2338.56    44.3  2338.5    57.5 2337.91    79.5 2335.81   101.5 2334.53
   119.6 2334.38   146.8 2333.69     189 2333.77     198 2333.96   215.9 2333.44
   229.3 2333.52   242.5 2334.31   252.3 2335.52   258.3 2335.67   260.1 2335.59
   264.5 2334.81   270.4 2333.01   273.3 2332.11   277.7 2331.82   282.1    2332
   285.5 2332.89   290.9 2334.44   295.3 2334.66   299.7 2334.64   308.6 2333.91
   311.8 2333.91   369.9 2335.62     400 2336.83   458.3 2337.55   487.1  2337.4
#Mann= 3 ,-1,0
       0     .05       0   270.4    .045       0   285.5     .05       0
#XS Ineff= 2 , 0
          121.05 2336.22  298.78         2336.16
Permanent Ineff=
       F       F
Bank Sta=270.4,285.5
XS Rating Curve= 0 ,0
Exp/Cntr(USF)=0,0
Exp/Cntr=0.3,0.1

Type RM Length L Ch R = 1 ,5054    ,171.8,171.1,169.8
XS GIS Cut Line= 3
2260424.27410568488493.1790561182260396.68055209488433.470121834
 2260101.8944326488170.336792033
#Sta/Elev= 30
       0  2337.4    47.9  2336.7    60.3 2336.12    77.2 2334.85   108.8 2331.88
   114.5 2331.56   138.3 2331.17   146.9 2331.23   157.6 2331.73   179.1 2331.46
   188.2 2329.52   192.4 2328.78   196.7 2328.71  201.312329.352   205.2 2330.06
   216.5 2330.16   222.4  2331.4   227.8 2332.21   230.7 2332.32   240.4  2331.9
   243.4 2331.95   248.8 2332.56   259.5 2332.73   270.2 2332.13   307.7 2331.88
   342.5 2332.52   388.2  2332.7   402.6 2333.15   436.4  2335.3   460.9 2335.65
#Mann= 3 ,-1,0
       0     .05       0   188.2    .045       0  201.31     .05       0
#XS Ineff= 2 , 0
                          231.83         2333.18
Permanent Ineff=
       F       F
Bank Sta=188.2,201.31
XS Rating Curve= 0 ,0
Exp/Cntr(USF)=0,0
Exp/Cntr=0.3,0.1

Type RM Length L Ch R = 1 ,4883    ,224.2,227.8,228
XS GIS Cut Line= 2
2260599.95460553 488355.720138262260203.71071334488073.759354456
#Sta/Elev= 30
       0 2331.26      39 2330.94    61.9 2331.23    79.1 2331.05   107.9 2331.28
   122.5 2330.51   142.2 2328.76   151.9 2328.17   156.6 2328.06   176.6  2328.8
   186.3 2329.55   196.1 2328.53   205.9 2328.84   213.9 2327.96   225.2 2327.95
     234 2327.46   240.3 2326.93   245.2 2327.57   248.3 2328.35     255 2329.28
   266.6 2329.03   279.9 2328.11   287.2 2328.12   294.1 2328.59   323.7  2329.5
   363.1 2329.59   425.2 2330.58   446.3  2331.4   474.9 2333.19   486.3 2333.63
#Mann= 5 ,-1,0
       0     .05       0     150     .07       0     234    .045       0
   245.2     .07       0     270     .05       0
#XS Ineff= 2 , 0
                          305.96         2331.39
Permanent Ineff=
       F       F
Bank Sta=234,245.2
XS Rating Curve= 0 ,0
Exp/Cntr(USF)=0,0
Exp/Cntr=0.3,0.1

Type RM Length L Ch R = 1 ,4655    ,161.5,162,162.6
XS GIS Cut Line= 4
2260656.05992246488243.1049052132260646.68347669488161.907104135
2260408.19085096487938.2780414832260307.45744711 487912.55199547
#Sta/Elev= 30
       0 2329.03    22.1 2328.74    50.3    2329    70.2 2328.75    92.5 2328.13
   117.9 2326.13   141.3 2325.81     151 2326.12155.40352325.692   157.6 2325.52
163.23922325.648   170.5 2326.05   177.4 2326.06   185.9 2325.82   194.8 2326.42
   197.2 2326.43   214.2 2326.06   223.2 2326.22   244.2 2326.07   258.2 2326.27
   269.9 2326.23   281.6 2325.82   293.3 2326.16   381.2 2327.12   403.2 2327.56
   449.1 2329.12   462.4 2330.01     483  2331.7   503.6 2332.91   512.6 2333.19
#Mann= 5 ,-1,0
       0     .05       0155.4035    .045       0163.2392     .05       0
  171.74     .07       0  311.74     .05       0
#XS Ineff= 2 , 0
                          336.88         2328.51
Permanent Ineff=
       F       F
Bank Sta=155.4035,163.2392
XS Rating Curve= 0 ,0
Exp/Cntr(USF)=0,0
Exp/Cntr=0.3,0.1

Type RM Length L Ch R = 1 ,4493    ,236.3,247.4,254.4
XS GIS Cut Line= 4
2260698.67415764488185.4057150262260709.43448564488006.522664366
2260584.41087774 487891.086574662260364.67807166487889.850778142
#Sta/Elev= 30
       0 2328.75    60.3 2327.48    76.4 2326.62    88.4 2326.32   108.4 2324.55
   124.5 2324.09   164.5 2324.83   168.5 2324.55   186.4 2324.45  216.83 2324.65
  238.64 2324.68   251.9 2325.43     283  2324.6   302.8 2325.03   328.6 2324.67
   346.3  2325.3   349.6 2325.16   385.6 2325.77   393.6 2326.48   401.6  2326.4
   409.6 2326.73   433.6 2326.36   441.6 2326.51   449.6 2326.21   453.6 2326.61
   465.6 2326.88   529.6 2327.89   541.6 2328.77   557.6 2329.33   569.1 2330.38
#Mann= 5 ,-1,0
       0     .05       0  189.21      .1       0  216.83    .045       0
  238.64     .08       0  329.21      .1       0
#XS Ineff= 2 , 0
                           337.2         2326.66
Permanent Ineff=
       F       F
Bank Sta=216.83,238.64
XS Rating Curve= 0 ,0
Exp/Cntr(USF)=0,0
Exp/Cntr=0.3,0.1

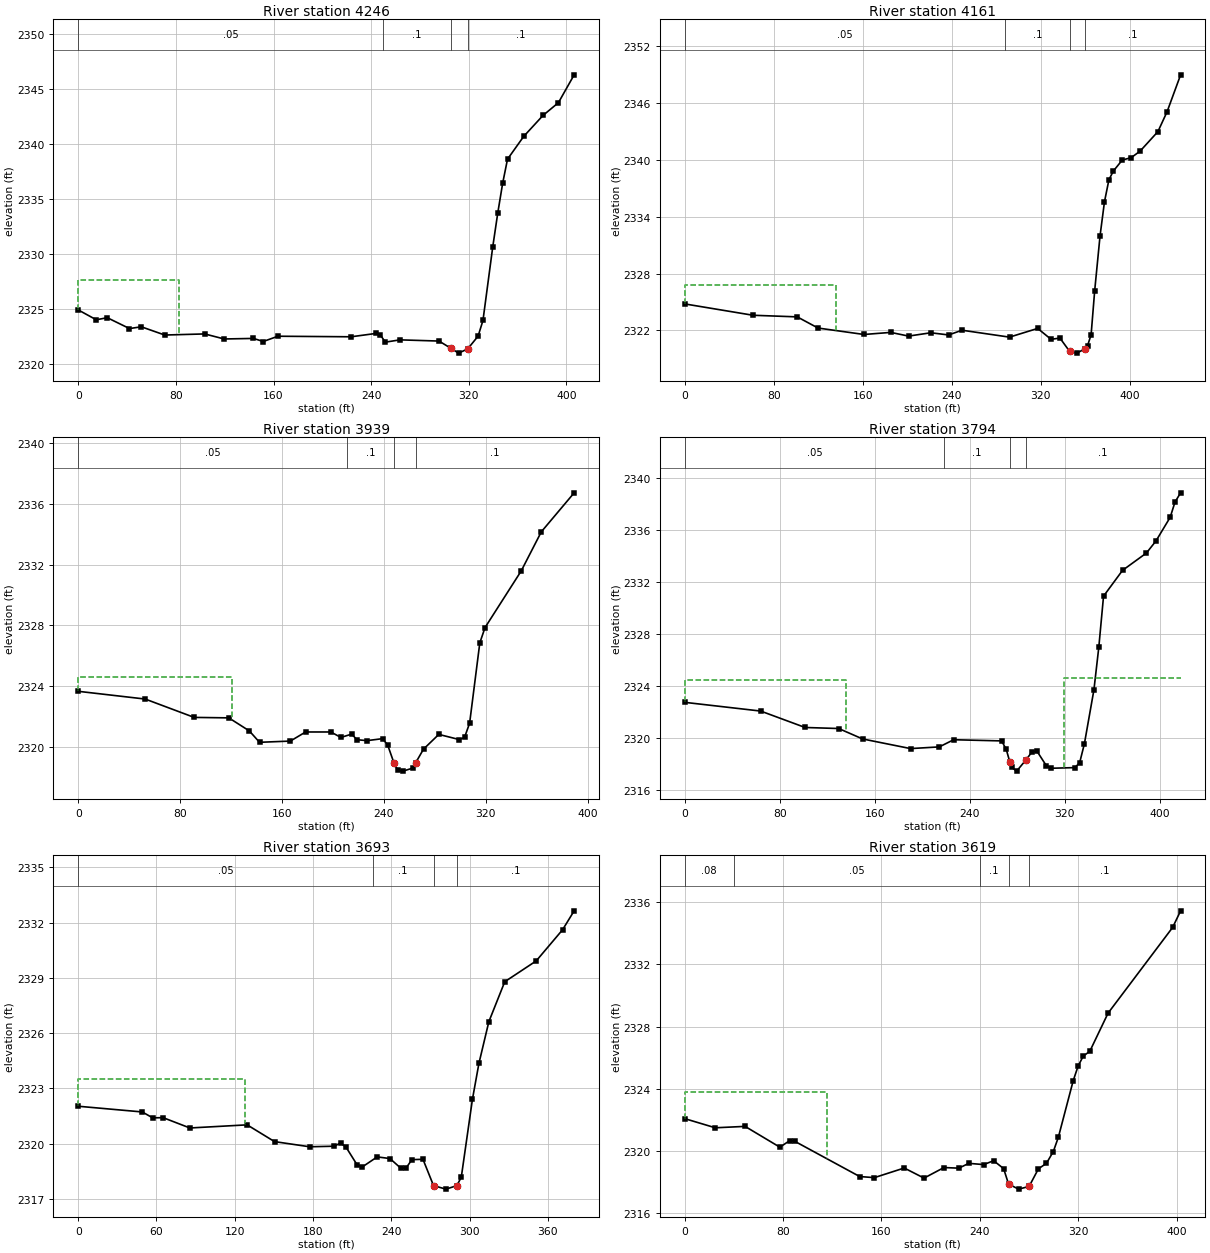
Type RM Length L Ch R = 1 ,4246    ,84.9,85.2,85.6
XS GIS Cut Line= 4
2260829.07021739488142.4572300242260855.76734195488089.062980905
2260849.10863413487790.0189158872260834.09493405487744.977815655
#Sta/Elev= 30
       0 2324.89    14.8 2323.99    23.8 2324.18      42 2323.19    51.7 2323.35
    70.9  2322.6   103.6  2322.7   119.6 2322.24   143.6 2322.29   151.6 2322.01
   163.6 2322.49   223.6 2322.44   243.6 2322.74   247.6  2322.6   251.6 2321.95
   263.6 2322.16   295.6 2322.05   305.42321.386   311.6 2320.95   319.12321.335
   327.6  2322.5   331.6 2323.93   339.6 2330.63   343.7 2333.71   347.7 2336.42
   351.7 2338.63     365 2340.71   380.8 2342.62   393.4 2343.78   406.3 2346.32
#Mann= 4 ,-1,0
       0     .05       0   249.7      .1       0   305.4    .045       0
   319.1      .1       0
#XS Ineff= 2 , 0
           82.23 2327.61
Permanent Ineff=
       F       F
Bank Sta=305.4,319.1
XS Rating Curve= 0 ,0
Exp/Cntr(USF)=0,0
Exp/Cntr=0.3,0.1

Type RM Length L Ch R = 1 ,4161    ,220.6,222,222.2
XS GIS Cut Line= 3
 2260901.6565844488179.6244328942260933.18535456488108.309357526
2260936.00184552487740.771686732
#Sta/Elev= 30
       0 2324.79    61.4 2323.59   101.1 2323.42   119.8 2322.24   161.1 2321.56
   185.1 2321.78   201.1 2321.39   221.1 2321.74   237.1 2321.51   249.1 2322.01
   291.8 2321.28   317.1  2322.2   329.1 2321.05   337.1 2321.18   345.7 2319.79
   352.2 2319.59   359.42320.032   361.9 2320.37   365.1 2321.54   368.3 2326.18
   373.1 2331.96   377.1 2335.58   381.1 2337.91   385.1 2338.83   393.1 2339.99
   401.1 2340.24   409.1 2340.93   425.1 2342.99   433.4 2345.11   445.5 2348.99
#Mann= 4 ,-1,0
       0     .05       0  287.97      .1       0   345.7    .045       0
   359.4      .1       0
#XS Ineff= 2 , 0
          136.07 2326.79
Permanent Ineff=
       F       F
Bank Sta=345.7,359.4
XS Rating Curve= 0 ,0
Exp/Cntr(USF)=0,0
Exp/Cntr=0.3,0.1

Type RM Length L Ch R = 1 ,3939    ,148.6,144.3,139.7
XS GIS Cut Line= 3
2261056.30333249488193.669641765 2261104.3581567488115.866593048
2261136.39470617487819.528510437
#Sta/Elev= 30
       0 2323.65    52.6 2323.14    91.1 2321.93   118.3  2321.9   134.4 2321.04
   142.4 2320.29   166.6 2320.37   178.6 2320.97   198.4 2320.97   206.3 2320.61
   214.8 2320.83   218.9 2320.46   226.9  2320.4     239 2320.53     243 2320.12
   248.1  2318.9   251.1 2318.44   255.1 2318.39   263.1  2318.6  265.09 2318.95
   271.2 2319.84   283.2 2320.81   299.3 2320.47   303.4 2320.61   307.4 2321.55
   315.4 2326.84   319.5 2327.85   347.9 2331.58   363.7 2334.16   389.5 2336.73
#Mann= 4 ,-1,0
       0     .05       0  211.45      .1       0   248.1    .045       0
  265.09      .1       0
#XS Ineff= 2 , 0
           121.1 2324.57
Permanent Ineff=
       F       F
Bank Sta=248.1,265.09
XS Rating Curve= 0 ,0
Exp/Cntr(USF)=0,0
Exp/Cntr=0.3,0.1

Type RM Length L Ch R = 1 ,3794    ,93.6,101.4,108.6
XS GIS Cut Line= 5
2261175.78930394 488189.092991842261245.15715342488133.747130885
2261269.29890373487953.3284728072261261.04136869487932.309292699
2261270.80027374487808.446267061
#Sta/Elev= 30
       0 2322.76      64 2322.09   101.4 2320.83   129.7 2320.75   149.8 2319.95
   190.2 2319.21   214.4 2319.34   226.5 2319.89   266.9  2319.8   270.8 2319.14
   273.8 2318.18   275.2 2317.78   279.5 2317.48   287.2 2318.32   292.4 2318.95
   296.5 2319.03   304.5  2317.9   308.5  2317.7   328.6 2317.75   332.6 2318.13
   336.6 2319.59   344.6 2323.72   348.7 2326.98   352.7 2330.91   368.7 2332.89
   388.8 2334.22   396.8 2335.14   408.8 2336.96   412.9 2338.14   417.6 2338.84
#Mann= 4 ,-1,0
       0     .05       0  218.74      .1       0   273.8    .045       0
   287.2      .1       0
#XS Ineff= 2 , 0
          136.07 2324.49  319.65         2324.66
Permanent Ineff=
       F       F
Bank Sta=273.8,287.2
XS Rating Curve= 0 ,0
Exp/Cntr(USF)=0,0
Exp/Cntr=0.3,0.1

Type RM Length L Ch R = 1 ,3693    ,76.8,74.4,72.4
XS GIS Cut Line= 4
2261297.85186316488218.1639083492261306.47833736488092.739825738
2261366.67576783487910.3233697992261373.36437121487848.301774779
#Sta/Elev= 30
       0 2322.03    49.1 2321.72    57.1  2321.4    65.1 2321.41    85.6 2320.85
   129.5 2321.02   150.5 2320.11   177.4 2319.83   196.4 2319.86   201.1 2320.04
   205.3 2319.81   213.7 2318.86   217.9 2318.74   229.2 2319.28     239 2319.19
   247.4 2318.66   251.6  2318.7   255.8 2319.13   264.3 2319.15   272.4 2317.72
   281.9 2317.53  290.34 2317.72   293.7 2318.19   302.2  2322.4   307.2 2324.36
   314.8 2326.62     327 2328.79   351.1 2329.92   371.3 2331.61   380.2 2332.64
#Mann= 4 ,-1,0
       0     .05       0  225.72      .1       0   272.4    .045       0
  290.34      .1       0
#XS Ineff= 2 , 0
          128.18 2323.53
Permanent Ineff=
       F       F
Bank Sta=272.4,290.34
XS Rating Curve= 0 ,0
Exp/Cntr(USF)=0,0
Exp/Cntr=0.3,0.1

Type RM Length L Ch R = 1 ,3619    ,205.1,207,206.1
XS GIS Cut Line= 2
2261387.58910976488233.8028258252261445.41298569487834.818081916
#Sta/Elev= 30
       0 2322.07    24.9 2321.48    49.1 2321.57    77.4 2320.23    85.5 2320.66
    89.5 2320.61   142.3 2318.34   154.2 2318.27   178.5 2318.89   194.6 2318.24
   210.8 2318.92   222.9 2318.88     231 2319.19   243.1 2319.11   251.2 2319.36
   259.3 2318.85   263.3 2317.86   271.4 2317.53     280  2317.7   287.6 2318.84
   294.1 2319.19   299.7 2319.95   303.8 2320.87   315.9 2324.52   319.9 2325.46
     324 2326.09   329.4 2326.41   344.2 2328.86   396.7 2334.38   403.2 2335.45
#Mann= 5 ,-1,0
       0     .08       0      40     .05       0     240      .1       0
   263.3    .045       0     280      .1       0
#XS Ineff= 2 , 0
          115.94 2323.78
Permanent Ineff=
       F       F
Bank Sta=263.3,280
XS Rating Curve= 0 ,0
Exp/Cntr(USF)=0,0
Exp/Cntr=0.3,0.1

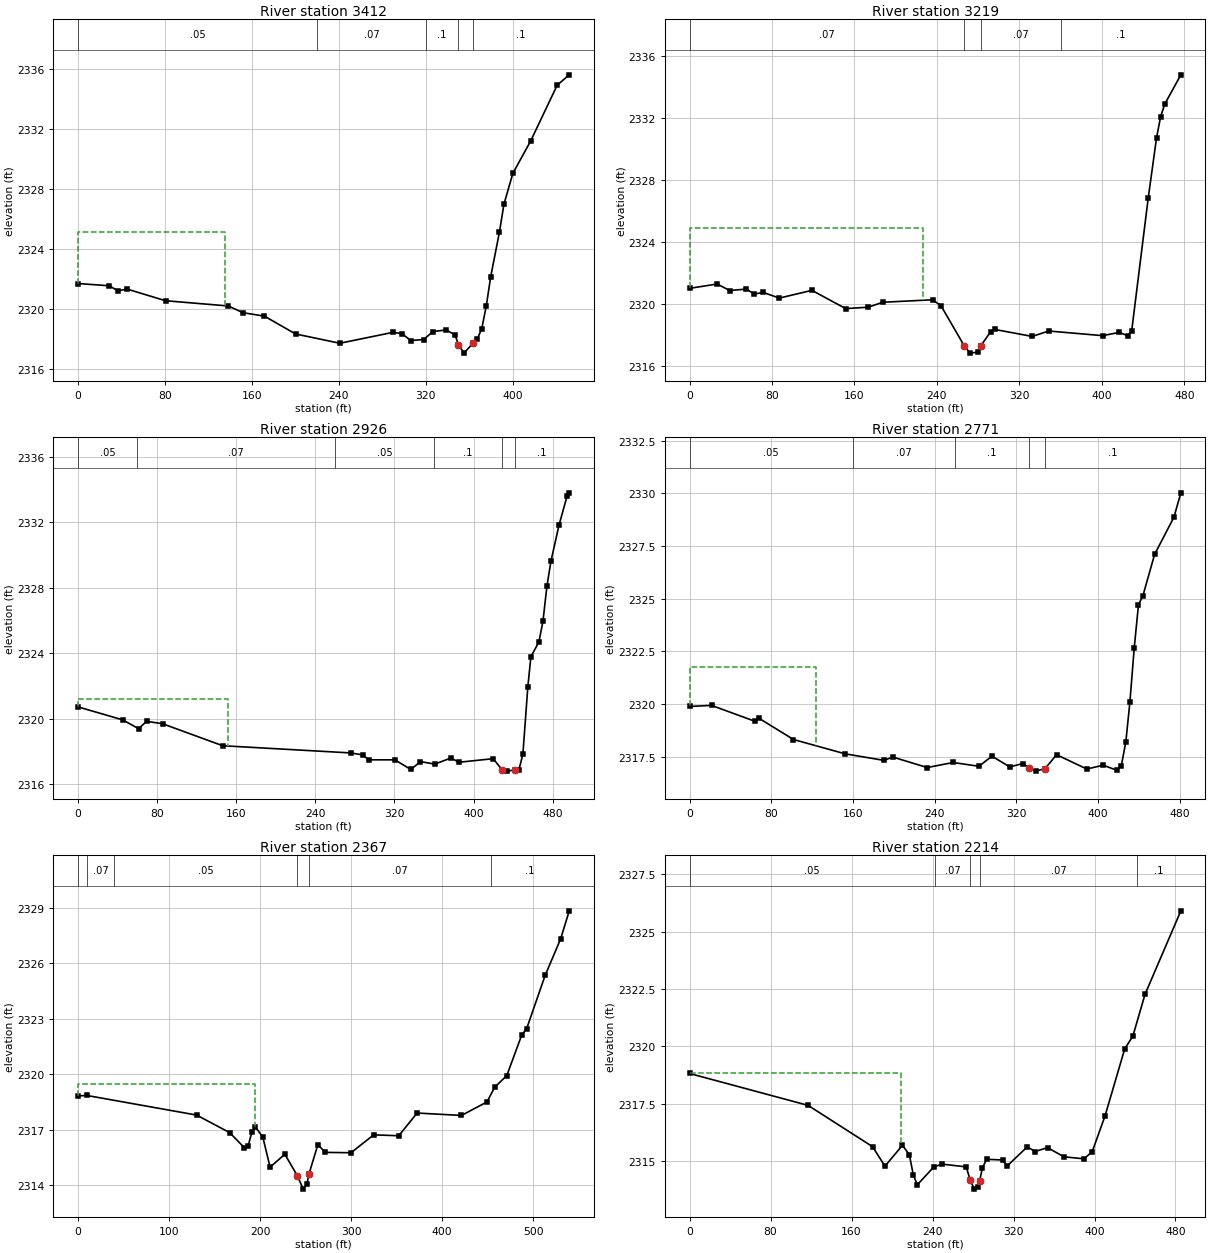
Type RM Length L Ch R = 1 ,3412    ,188.2,192.4,180.9
XS GIS Cut Line= 2
2261553.27600491488313.3320689552261643.28628912487870.321941737
#Sta/Elev= 30
       0  2321.7    28.7 2321.55    36.9 2321.21    45.1 2321.33    80.6 2320.55
   138.3  2320.2   151.9 2319.75   171.6 2319.52   200.2 2318.33     241 2317.71
     290 2318.44   298.1 2318.35   306.3 2317.89   318.1 2317.96   326.7 2318.49
   338.9  2318.6   347.1 2318.26  350.082317.611   355.3 2317.05   363.4 2317.71
   367.5    2318   371.6 2318.69   375.8 2320.23   379.8 2322.15   387.9 2325.16
     392    2327   400.2 2329.06   416.5 2331.21     441 2334.95   452.1 2335.64
#Mann= 5 ,-1,0
       0     .05       0     220     .07       0     320      .1       0
  350.08    .045       0   363.4      .1       0
#XS Ineff= 2 , 0
          135.27 2325.11
Permanent Ineff=
       F       F
Bank Sta=350.08,363.4
XS Rating Curve= 0 ,0
Exp/Cntr(USF)=0,0
Exp/Cntr=0.3,0.1

Type RM Length L Ch R = 1 ,3219    ,289.4,292.9,283.3
XS GIS Cut Line= 2
2261700.62445986488355.8672505742261749.56657307487881.655421419
#Sta/Elev= 30
       0    2321    26.8 2321.28    38.9 2320.86      55 2320.95      63 2320.63
    71.3 2320.74    87.1 2320.37   118.7 2320.87   151.5 2319.69   173.4 2319.78
   187.4  2320.1   235.9 2320.26     244 2319.87  266.45 2317.29   272.1 2316.81
   280.2 2316.88   282.7 2317.29   292.2  2318.2   296.3 2318.34   332.4 2317.89
   348.5 2318.24   400.8 2317.94   416.9 2318.15     425 2317.94     429 2318.25
     445 2326.82   453.1 2330.73   457.1 2332.11   461.1 2332.92   476.7 2334.81
#Mann= 4 ,-1,0
       0     .07       0  266.45    .045       0   282.7     .07       0
     360      .1       0
#XS Ineff= 2 , 0
          226.74  2324.9
Permanent Ineff=
       F       F
Bank Sta=266.45,282.7
XS Rating Curve= 0 ,0
Exp/Cntr(USF)=0,0
Exp/Cntr=0.3,0.1

Type RM Length L Ch R = 1 ,2926    ,152,155.6,156.9
XS GIS Cut Line= 2
2261805.29889438488353.7624768692261881.75195344487862.920485618
#Sta/Elev= 30
       0 2320.73    45.1 2319.94    61.3  2319.4    69.4 2319.85    85.6  2319.7
   146.3 2318.36   275.9 2317.92     288  2317.8   293.8  2317.5   320.4  2317.5
   336.6 2316.91   346.3 2317.39   360.9 2317.24   377.1 2317.61   385.2 2317.35
   419.8 2317.57   428.8  2316.9   433.6 2316.81   441.8 2316.88   445.9  2316.9
   449.9 2317.84   454.9 2321.95     458 2323.79   466.1 2324.69   470.2 2325.95
   474.2 2328.09   478.3 2329.62   486.4 2331.81   494.5 2333.57   496.8 2333.79
#Mann= 6 ,-1,0
       0     .05       0      60     .07       0     260     .05       0
     360      .1       0   428.8    .045       0   441.8      .1       0
#XS Ineff= 2 , 0
          151.99 2321.22
Permanent Ineff=
       F       F
Bank Sta=428.8,441.8
XS Rating Curve= 0 ,0
Exp/Cntr(USF)=0,0
Exp/Cntr=0.3,0.1

Type RM Length L Ch R = 1 ,2771    ,406.3,403.4,401.1
XS GIS Cut Line= 2
2261874.41991673488345.5548104812262029.54978032487889.982059552
#Sta/Elev= 30
       0 2319.88    21.5 2319.93    63.8 2319.18    68.3 2319.31   101.8 2318.31
   152.5 2317.63   190.5 2317.32     199 2317.48   232.8 2316.98   258.2 2317.22
   283.5 2317.04   296.2 2317.52   313.7 2317.01   326.4 2317.17   332.7 2316.96
     339 2316.81  348.24 2316.93   359.6 2317.59   389.1 2316.91   405.2 2317.09
   418.7 2316.85     423 2317.07   427.4  2318.2   431.4  2320.1   435.6 2322.65
   439.8 2324.71   444.1 2325.13   455.6  2327.1   474.5 2328.86   481.3 2330.02
#Mann= 5 ,-1,0
       0     .05       0     160     .07       0     260      .1       0
   332.7    .045       0  348.24      .1       0
#XS Ineff= 2 , 0
          123.99 2321.73
Permanent Ineff=
       F       F
Bank Sta=332.7,348.24
XS Rating Curve= 0 ,0
Exp/Cntr(USF)=0,0
Exp/Cntr=0.3,0.1

Type RM Length L Ch R = 1 ,2367    ,153.4,153.2,151.2
XS GIS Cut Line= 4
2262028.54782666488403.7644368142262115.66435797488327.769164818
2262149.95490753488071.9802005372262207.41474733487916.282570105
#Sta/Elev= 30
       0 2318.83      10 2318.85   130.3 2317.79   166.6 2316.84   182.8 2316.02
   186.8  2316.1   190.9 2316.85   194.9 2317.14     203  2316.6     211 2314.97
   227.2 2315.67     2412314.499   247.4 2313.78   251.4 2314.04   253.6 2314.58
   263.5 2316.19   271.6 2315.77   299.9 2315.75   324.8 2316.72   352.3 2316.67
   372.5  2317.9   421.2 2317.77   449.2  2318.5   457.7  2319.3     471 2319.93
   487.5 2322.14   492.8 2322.47   513.1 2325.35   530.2 2327.34   539.6 2328.85
#Mann= 6 ,-1,0
       0     .05       0      10     .07       0      40     .05       0
     241    .045       0   253.6     .07       0  453.68      .1       0
#XS Ineff= 2 , 0
           194.2 2319.47
Permanent Ineff=
       F       F
Bank Sta=241,253.6
XS Rating Curve= 0 ,0
Exp/Cntr(USF)=0,0
Exp/Cntr=0.3,0.1

Type RM Length L Ch R = 1 ,2214    ,108.8,107.5,106.6
XS GIS Cut Line= 3
2262182.39191387488423.2266406182262252.82655621488299.966016526
2262283.41001933487957.987292542
#Sta/Elev= 30
       0 2318.82   117.1 2317.43   180.8 2315.63     193 2314.78   210.3 2315.69
   217.1 2315.28   221.1 2314.38     225 2313.97   241.1 2314.74   249.2 2314.87
   273.3 2314.75   277.3 2314.16   281.3 2313.78   285.3 2313.89   286.62314.156
   289.3 2314.71   293.4 2315.08   309.4 2315.05   313.5 2314.78   333.5 2315.62
   341.5 2315.42   353.6 2315.59   369.7 2315.19   389.7  2315.1   397.8 2315.42
   410.4 2316.97   429.9  2319.9   437.9 2320.45   449.9 2322.27   485.3 2325.91
#Mann= 5 ,-1,0
       0     .05       0  241.97     .07       0   277.3    .045       0
   286.6     .07       0  441.97      .1       0
#XS Ineff= 2 , 0
          209.34 2318.83
Permanent Ineff=
       F       F
Bank Sta=277.3,286.6
XS Rating Curve= 0 ,0
Exp/Cntr(USF)=0,0
Exp/Cntr=0.3,0.1