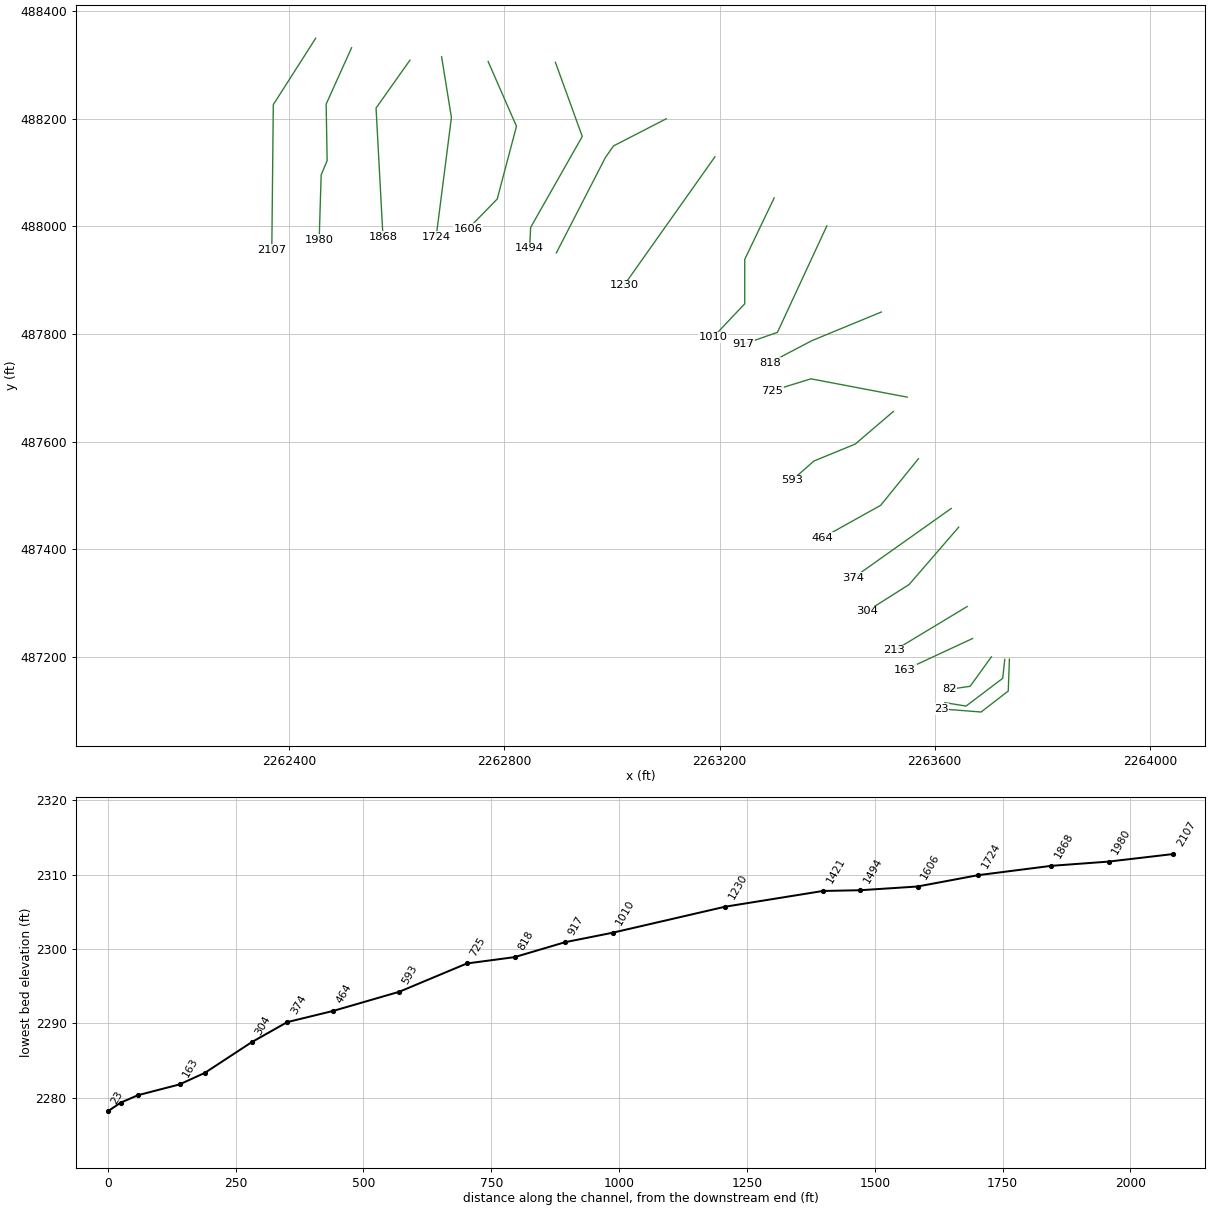
HEC-RAS study GLADERN.prj: GLADERN

--- GLADERN.g01 (geometry) --- (continued)

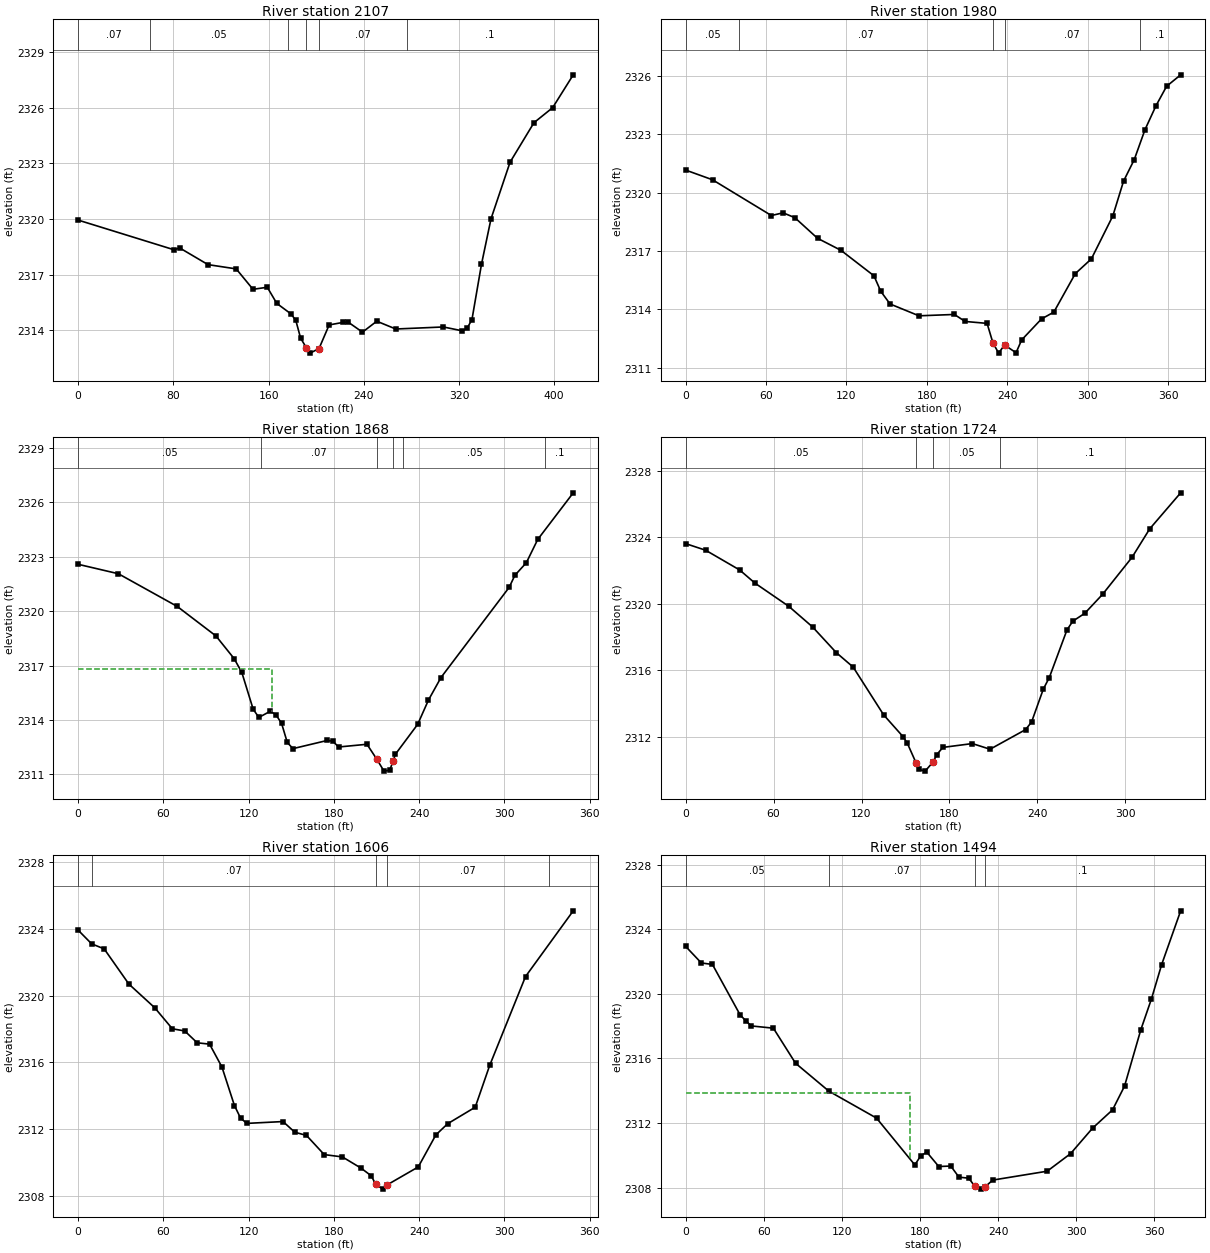
Type RM Length L Ch R = 1 ,2107    ,131.1,126.8,122.2
XS GIS Cut Line= 3
2262449.30213747488349.0849118412262370.52655064488225.824287749
2262367.74623581487956.133749323
#Sta/Elev= 30
       0 2319.94    80.6 2318.34    85.3 2318.44   109.1 2317.54   132.8 2317.31
   146.9 2316.21   158.9 2316.32   166.9 2315.45   178.9 2314.88   182.9 2314.53
   186.9 2313.58   191.62313.073   194.9 2312.77   202.42313.019   210.9 2314.29
   222.9 2314.43   226.9 2314.44   238.9  2313.9   250.9 2314.49   266.9 2314.07
   306.9 2314.18   322.9 2313.97   326.9 2314.12   330.9 2314.58   338.9 2317.56
   346.9 2320.01   362.9 2323.06     383 2325.19   398.7    2326     416 2327.77
#Mann= 6 ,-1,0
       0     .07       0      60     .05       0  176.28     .07       0
   191.6    .045       0   202.4     .07       0  276.28      .1       0
Bank Sta=191.6,202.4
XS Rating Curve= 0 ,0
Exp/Cntr(USF)=0,0
Exp/Cntr=0.3,0.1

Type RM Length L Ch R = 1 ,1980    ,107.5,112.2,114.9
XS GIS Cut Line= 5
2262516.02969337488331.4762512572262468.76434127488226.751059359
2262470.61788449488122.0258674612262459.49662517 488095.14949078
2262455.78953873487974.669181517
#Sta/Elev= 30
       0 2321.17    20.1 2320.67      64 2318.83    72.7 2318.97    81.5 2318.72
    98.4 2317.66   115.9 2317.04   140.5 2315.73   145.6 2314.93   152.5 2314.28
   174.1 2313.67   200.5 2313.74   208.5 2313.38   224.9 2313.28   229.2 2312.29
   233.5 2311.75   237.9 2312.17   246.5 2311.77   250.7 2312.43   265.5 2313.51
   274.7 2313.86   290.7 2315.84   302.7  2316.6   318.7 2318.81   326.7  2320.6
   334.7 2321.71   342.7 2323.25   350.9 2324.48   358.8 2325.48   369.3 2326.07
#Mann= 5 ,-1,0
       0     .05       0      40     .07       0   229.2    .045       0
   237.9     .07       0  338.73      .1       0
Bank Sta=229.2,237.9
XS Rating Curve= 0 ,0
Exp/Cntr(USF)=0,0
Exp/Cntr=0.3,0.1

Type RM Length L Ch R = 1 ,1868    ,145.3,143.5,141.5
XS GIS Cut Line= 3
 2262624.4619717488308.3069610142262561.51935106488219.414735296
2262574.41630478487980.229811175
#Sta/Elev= 30
       0 2322.58    28.3 2322.06    69.7 2320.26      97 2318.63   109.8 2317.38
   115.2 2316.62   123.2 2314.59   127.2 2314.14   135.2 2314.48   139.2 2314.29
   143.2 2313.81   147.2 2312.76   151.2 2312.42   175.3 2312.87   179.3 2312.83
   183.3 2312.51   203.3 2312.66   210.1 2311.85   215.3 2311.18   219.3 2311.23
  221.84 2311.76   223.3 2312.11     239 2313.76   246.6  2315.1   255.4 2316.34
   303.4 2321.31   307.4 2321.97   315.5 2322.67   323.5 2323.95   348.5 2326.52
#Mann= 6 ,-1,0
       0     .05       0  128.92     .07       0   210.1    .045       0
  221.84     .07       0  228.92     .05       0  328.92      .1       0
#XS Ineff= 2 , 0
          136.39 2316.83
Permanent Ineff=
       F       F
Bank Sta=210.1,221.84
XS Rating Curve= 0 ,0
Exp/Cntr(USF)=0,0
Exp/Cntr=0.3,0.1

Type RM Length L Ch R = 1 ,1724    ,119.4,118,116.5
XS GIS Cut Line= 3
2262683.38611065 488314.689637092262701.62775624488201.861681008
 2262673.2518631487980.259467867
#Sta/Elev= 30
       0 2323.63    13.7 2323.23    36.9 2322.04    47.3 2321.25    70.4 2319.85
    86.6 2318.61   102.8 2317.06   114.3 2316.19   135.1 2313.31   148.4 2311.99
   151.3 2311.59   157.2 2310.42   159.3 2310.02   163.4 2309.92   168.9 2310.48
   171.4 2310.92   175.5 2311.35   195.6 2311.58   207.7 2311.24   231.9 2312.42
     236 2312.88     244 2314.86   248.1 2315.56   260.2 2318.44   264.2 2318.96
   272.3 2319.43   284.4 2320.57   304.5  2322.8   316.6 2324.52   337.7 2326.69
#Mann= 4 ,-1,0
       0     .05       0   157.2    .045       0   168.9     .05       0
  214.29      .1       0
Bank Sta=157.2,168.9
XS Rating Curve= 0 ,0
Exp/Cntr(USF)=0,0
Exp/Cntr=0.3,0.1

Type RM Length L Ch R = 1 ,1606    ,113.6,112.1,109.8
XS GIS Cut Line= 4
2262769.86502309488305.9066225452262822.56311037488185.646884925
2262786.75543568488050.523584229 2262732.7061154487995.123030943
#Sta/Elev= 30
       0 2323.92     9.5  2323.1    18.3  2322.8    35.7 2320.69    53.9 2319.27
    66.3 2318.01      75 2317.88    83.8 2317.17    92.5 2317.09   101.2 2315.72
     110 2313.41   114.3 2312.66   118.7 2312.34   144.2 2312.45   152.5 2311.81
   160.7 2311.62   173.2 2310.47     186 2310.33   199.1 2309.66   206.3  2309.2
  209.43 2308.69   214.5  2308.4   217.4 2308.65   239.4 2309.73   251.8 2311.65
   260.1 2312.32   279.5 2313.31   289.7 2315.82   314.9 2321.14   348.5 2325.08
#Mann= 5 ,-1,0
       0     .05       0      10     .07       0  209.43    .045       0
   217.4     .07       0  331.09      .1       0
Bank Sta=209.43,217.4
XS Rating Curve= 0 ,0
Exp/Cntr(USF)=0,0
Exp/Cntr=0.3,0.1

Type RM Length L Ch R = 1 ,1494    ,71.1,72.8,72.4
XS GIS Cut Line= 4
2262894.85407624488304.5553895382262944.84969749488166.729622827
  2262848.912154487997.8254969572262846.88530449487958.639739755
#Sta/Elev= 30
       0 2322.94    12.1 2321.91    20.6 2321.82    41.9 2318.69    46.1 2318.34
    50.4 2318.01    67.4 2317.87    84.4  2315.7     110 2313.97   146.6  2312.3
     176  2309.4   180.6 2309.97   185.2 2310.19   194.4  2309.3   203.6 2309.33
   209.9 2308.64   217.4 2308.58     222 2308.08   226.6  2307.9   229.92308.039
   235.8 2308.46   277.6 2309.01   295.6  2310.1   312.5 2311.68   327.8 2312.81
     337 2314.28   349.5 2317.77   357.7 2319.69   365.5 2321.81   380.1 2325.14
#Mann= 4 ,-1,0
       0     .05       0     110     .07       0     222    .045       0
   229.9      .1       0
#XS Ineff= 2 , 0
          171.98 2313.84
Permanent Ineff=
       F       F
Bank Sta=222,229.9
XS Rating Curve= 0 ,0
Exp/Cntr(USF)=0,0
Exp/Cntr=0.3,0.1

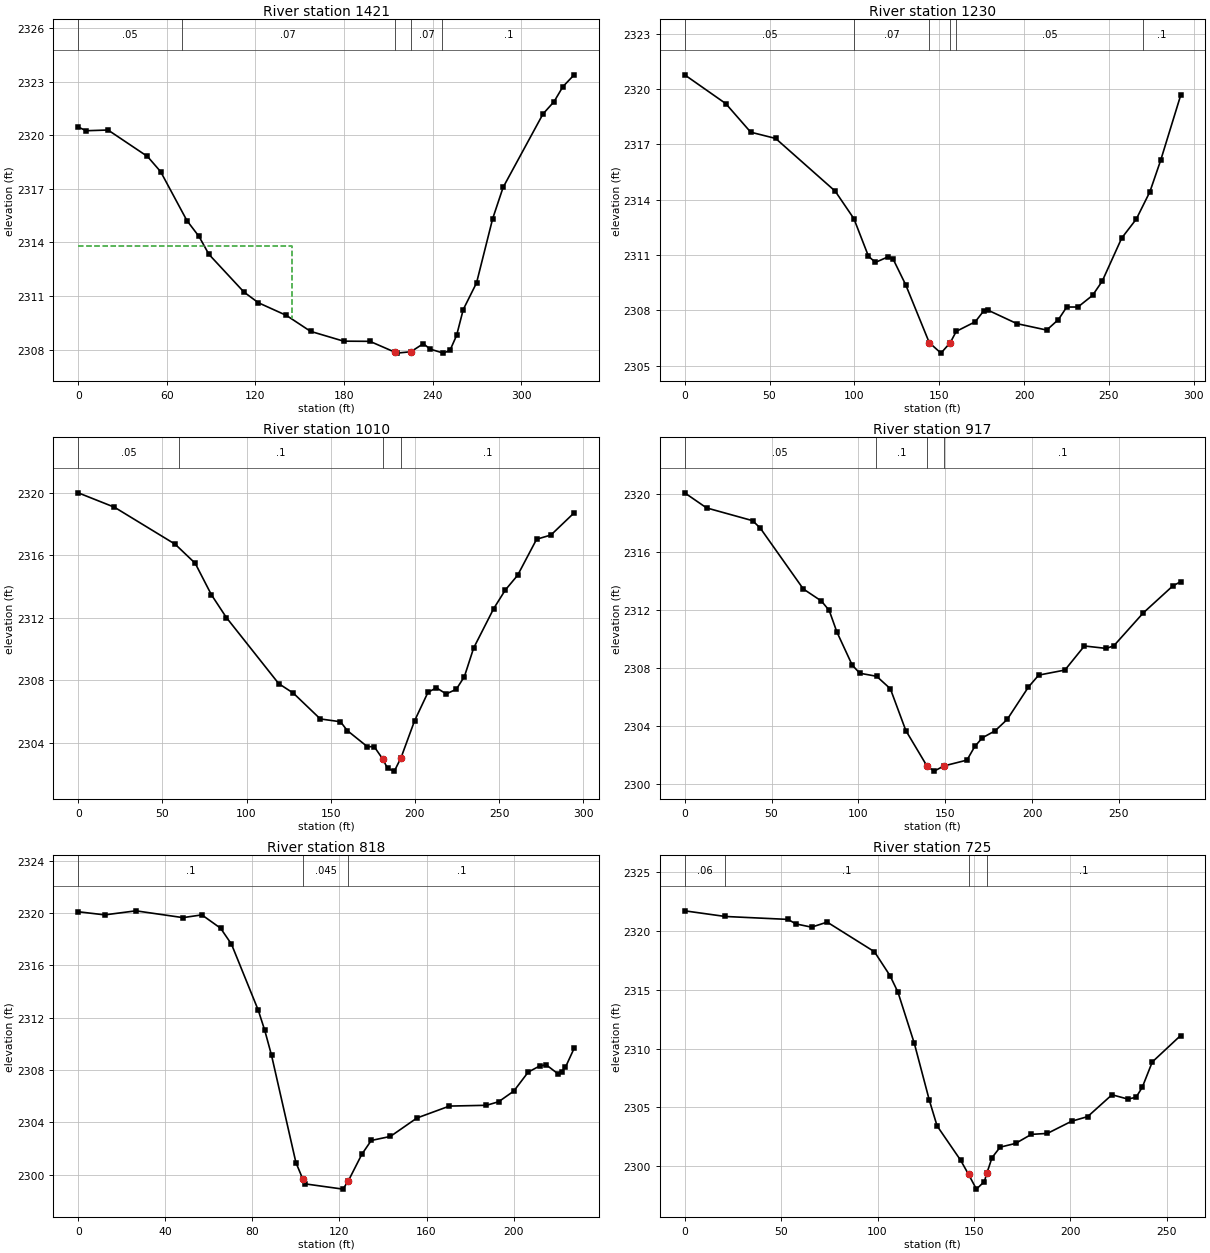
Type RM Length L Ch R = 1 ,1421    ,191.2,191.6,184.7
XS GIS Cut Line= 4
2263100.97277845488199.5168896422263002.95271679488149.163593737
2262987.80960046488127.5759937942262896.68596813487950.418508329
#Sta/Elev= 30
       0 2320.46     5.3 2320.25    20.2 2320.29    46.9 2318.81    55.8 2317.96
    73.6 2315.22    81.8 2314.33    88.5 2313.33   112.2 2311.22     122 2310.62
     141 2309.91   157.3 2309.02   179.7 2308.47   197.5 2308.46   214.5 2307.85
   215.7  2307.8225.24512307.877   233.7 2308.33   238.2 2308.03   247.2  2307.8
   251.7 2307.95   256.2 2308.79   260.7 2310.24   269.7 2311.73   280.6 2315.32
   287.7 2317.08   314.7 2321.19   322.2 2321.88   328.2 2322.72   335.8 2323.38
#Mann= 5 ,-1,0
       0     .05       0      70     .07       0   214.5    .045       0
225.2451     .07       0  246.57      .1       0
#XS Ineff= 2 , 0
          144.85 2313.82
Permanent Ineff=
       F       F
Bank Sta=214.5,225.2451
XS Rating Curve= 0 ,0
Exp/Cntr(USF)=0,0
Exp/Cntr=0.3,0.1

Type RM Length L Ch R = 1 ,1230    ,213.3,220,225.9
XS GIS Cut Line= 2
2263191.44972127488128.895098632 2263022.5455954487890.402472904
#Sta/Elev= 30
       0 2320.77    24.2 2319.21    38.9 2317.66    53.6 2317.32    88.7 2314.46
    99.7 2312.97   108.3 2310.93   112.4  2310.6   119.8  2310.9   122.7  2310.8
   130.2 2309.39   144.1 2306.25     151 2305.68   156.5 2306.25     160 2306.86
   171.2 2307.38   176.1 2307.96   178.7 2308.01   195.7 2307.28   213.3 2306.93
   220.2  2307.5   225.1 2308.18   231.7 2308.18   240.3 2308.81     246 2309.58
   257.5 2311.92   266.1 2312.95   274.1 2314.43   280.5 2316.15   292.2 2319.65
#Mann= 6 ,-1,0
       0     .05       0     100     .07       0   144.1    .045       0
   156.5     .07       0     160     .05       0     270      .1       0
Bank Sta=144.1,156.5
XS Rating Curve= 0 ,0
Exp/Cntr(USF)=0,0
Exp/Cntr=0.3,0.1

Type RM Length L Ch R = 1 ,1010    ,97.6,92.8,88.9
XS GIS Cut Line= 4
2263301.57521133488052.5504337392263246.85027455487938.371244651
2263246.85027455487855.9460312262263188.07163875487793.789312906
#Sta/Elev= 30
       0 2319.99    21.5 2319.07    57.6  2316.7    69.5 2315.48    79.1 2313.47
      88 2312.01   119.1 2307.78   127.8 2307.17   143.8 2305.52   155.8 2305.34
   159.8 2304.78   171.8 2303.74   175.8 2303.75   180.82302.969   183.8 2302.35
   187.8 2302.18   191.8 2303.05   199.8  2305.4   207.8 2307.23   212.8 2307.51
   218.6 2307.12   224.6 2307.42   229.4 2308.23   234.9 2310.06   246.8 2312.58
   253.7 2313.77     261 2314.71   272.3 2317.02   280.8 2317.29   294.6 2318.71
#Mann= 4 ,-1,0
       0     .05       0      60      .1       0   180.8    .045       0
   191.8      .1       0
Bank Sta=180.8,191.8
XS Rating Curve= 0 ,0
Exp/Cntr(USF)=0,0
Exp/Cntr=0.3,0.1

Type RM Length L Ch R = 1 ,917     ,106.5,98.8,91.4
XS GIS Cut Line= 3
2263399.46461874 488000.599965942263307.66343332 487802.94639324
 2263243.9646516487780.464470279
#Sta/Elev= 30
       0  2320.1    12.6 2319.06    39.1 2318.18    43.5 2317.67    68.3 2313.47
    78.7 2312.64    83.2 2311.99    87.6 2310.51    96.4 2308.23   100.8 2307.66
   110.5 2307.45   118.4 2306.59   127.3 2303.71  139.542301.251   143.6 2300.91
   149.3 2301.27   162.5 2301.67     167 2302.61   171.4 2303.21   178.7 2303.69
   185.7 2304.48   197.9 2306.71   203.8 2307.53   218.9 2307.88   230.1 2309.54
   242.8 2309.37   247.1 2309.56     264 2311.82     281 2313.68   285.5 2313.97
#Mann= 4 ,-1,0
       0     .05       0     110      .1       0  139.54    .045       0
   149.3      .1       0
Bank Sta=139.54,149.3
XS Rating Curve= 0 ,0
Exp/Cntr(USF)=0,0
Exp/Cntr=0.3,0.1

Type RM Length L Ch R = 1 ,818     ,99.6,93.2,86.7
XS GIS Cut Line= 3
2263500.64973534487840.5749450322263371.83932769487787.519253945
2263293.46781329487746.496157662
#Sta/Elev= 30
       0 2320.11    12.2 2319.87    26.5 2320.18    48.1 2319.66    56.8 2319.87
    65.4 2318.85    70.4 2317.63    82.7 2312.58    85.7 2311.03    88.8 2309.13
     100 2300.93  103.18 2299.66   104.3  2299.3   121.6  2298.9   124.1 2299.54
   130.3 2301.57   134.6 2302.62   143.4 2302.93   155.6 2304.34   170.5 2305.25
   187.5 2305.31   193.1 2305.58   200.1  2306.4   206.7 2307.85   211.9 2308.31
   214.9 2308.41   220.2 2307.74     222 2307.88   223.8 2308.22   227.8 2309.67
#Mann= 3 ,-1,0
       0      .1       0  103.18    .045       0   124.1      .1       0
Bank Sta=103.18,124.1
XS Rating Curve= 0 ,0
Exp/Cntr(USF)=0,0
Exp/Cntr=0.3,0.1

Type RM Length L Ch R = 1 ,725     ,125.8,132.4,140.2
XS GIS Cut Line= 3
2263548.79577408487682.5535925712263370.00940561487716.537778312
2263298.10083868487694.374178916
#Sta/Elev= 30
       0 2321.73      21 2321.25    53.6    2321    57.6 2320.62    65.8 2320.34
    73.9 2320.77    98.4 2318.25   106.5 2316.21   110.6 2314.81   119.1 2310.45
   126.9  2305.6   130.9 2303.43   143.1 2300.51   147.2 2299.31   151.3 2298.05
   155.4 2298.69   156.7  2299.4   159.4 2300.73   163.6 2301.62   171.6 2301.94
   179.8 2302.71   188.1 2302.79   200.7 2303.83     209 2304.22   221.6 2306.08
   229.9 2305.71   234.1 2305.87   237.3 2306.71   242.5 2308.87   257.2 2311.12
#Mann= 4 ,-1,0
       0     .06       0      21      .1       0   147.2    .045       0
   156.7      .1       0
Bank Sta=147.2,156.7
XS Rating Curve= 0 ,0
Exp/Cntr(USF)=0,0
Exp/Cntr=0.3,0.1

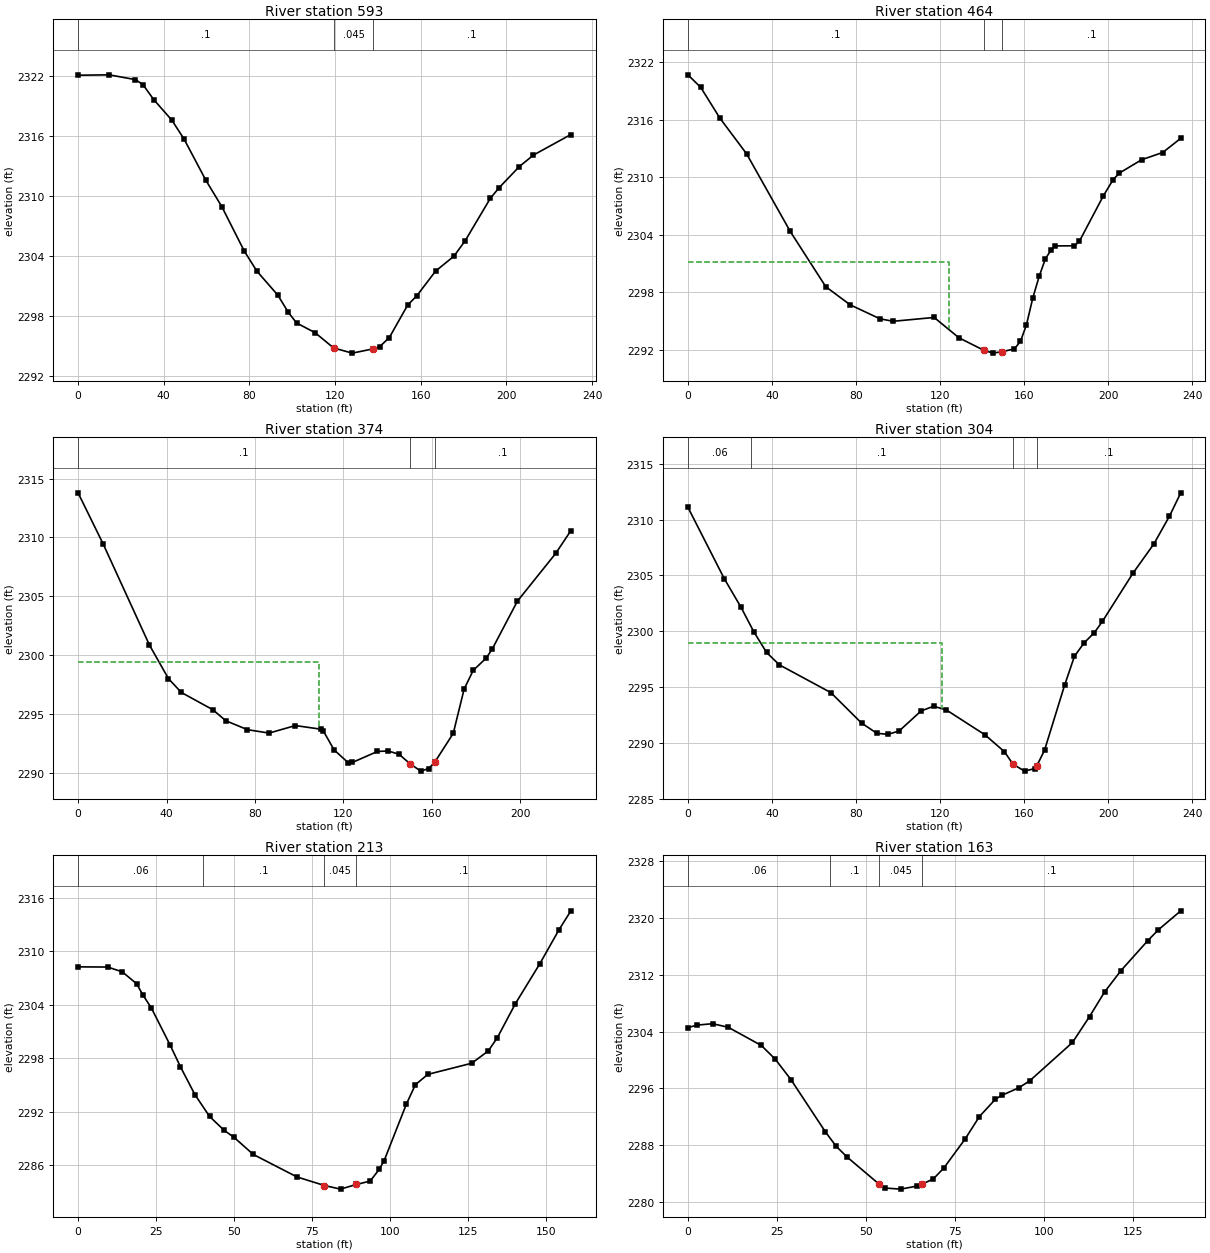
Type RM Length L Ch R = 1 ,593     ,127.7,129,130
XS GIS Cut Line= 4
2263523.18450366487655.9572732942263452.26098559487595.376768277
2263375.42717435 487563.855204692263335.04017101487528.393445655
#Sta/Elev= 30
       0 2322.04    14.5 2322.08    26.8  2321.6    30.3  2321.1    35.3 2319.61
    43.8 2317.54    49.5 2315.65    59.7 2311.52    67.1  2308.9    77.6 2304.45
    83.5 2302.44    93.3 2300.03    98.1 2298.34     102 2297.26   110.7 2296.28
   119.3 2294.76     128 2294.24   137.9 2294.67   140.9  2294.9   145.3 2295.79
   153.9 2299.05   158.2 2299.99   166.9 2302.44   175.5 2303.94   180.7 2305.47
   192.5 2309.73   196.6 2310.79     206  2312.9   212.6 2314.05   230.1 2316.11
#Mann= 3 ,-1,0
       0      .1       0   119.3    .045       0   137.9      .1       0
Bank Sta=119.3,137.9
XS Rating Curve= 0 ,0
Exp/Cntr(USF)=0,0
Exp/Cntr=0.3,0.1

Type RM Length L Ch R = 1 ,464     ,88.4,90,90.8
XS GIS Cut Line= 3
 2263569.7395353487568.1420560212263499.54333097487481.603624706
2263391.97064442487421.690449691
#Sta/Elev= 30
       0 2320.69     6.1 2319.38    15.2 2316.18    27.9 2312.46    48.7 2304.36
    65.6  2298.6    77.2 2296.71    91.4 2295.25    97.7 2294.99   117.2 2295.39
     129 2293.27  140.73 2291.98   145.2 2291.67   149.5 2291.82   155.4 2292.11
   158.3  2292.9   161.1 2294.59   164.2 2297.45   167.2 2299.68   170.2 2301.53
     173 2302.46   174.8 2302.85     184 2302.86   186.3 2303.32   197.7 2308.05
   202.4 2309.76   205.4 2310.45     216 2311.84     226 2312.59   234.6 2314.07
#Mann= 3 ,-1,0
       0      .1       0  140.73    .045       0   149.5      .1       0
#XS Ineff= 2 , 0
          124.17 2301.18
Permanent Ineff=
       F       F
Bank Sta=140.73,149.5
XS Rating Curve= 0 ,0
Exp/Cntr(USF)=0,0
Exp/Cntr=0.3,0.1

Type RM Length L Ch R = 1 ,374     ,70.3,69.6,69.1
XS GIS Cut Line= 2
 2263630.6511325487475.771460065 2263448.7907121487346.910362179
#Sta/Elev= 30
       0 2313.79    11.4 2309.43    32.3 2300.86    40.9 2298.01    46.7 2296.84
      61 2295.37    66.8 2294.44    76.6 2293.68    86.4 2293.39    98.3 2294.03
   109.8 2293.72   110.9 2293.58   115.8 2291.96   122.1 2290.89   124.1  2290.9
   135.4 2291.83   140.3 2291.87   145.2 2291.59   150.1 2290.79     155 2290.16
   158.6 2290.38   161.4 2290.94   169.7 2293.37   174.6 2297.12   178.7 2298.71
   184.6 2299.76   187.3 2300.52   198.7 2304.59     216 2308.64   222.9 2310.58
#Mann= 3 ,-1,0
       0      .1       0   150.1    .045       0   161.4      .1       0
#XS Ineff= 2 , 0
           109.1 2299.44
Permanent Ineff=
       F       F
Bank Sta=150.1,161.4
XS Rating Curve= 0 ,0
Exp/Cntr(USF)=0,0
Exp/Cntr=0.3,0.1

Type RM Length L Ch R = 1 ,304     ,91.6,91.4,91.1
XS GIS Cut Line= 3
2263644.66027109 487441.14119638 2263552.2434451487334.338819826
2263473.37101102487284.529498057
#Sta/Elev= 30
       0 2311.11    17.3 2304.71    25.2 2302.17    31.3 2299.97    37.4  2298.1
    43.5 2296.99      68  2294.5    82.6 2291.77    89.9 2290.85    95.2 2290.76
   100.5 2291.06   110.9 2292.85   116.9 2293.28     123 2292.94   141.3 2290.72
   150.6  2289.2  154.67 2288.08   160.2 2287.46     165 2287.69   165.9 2287.89
   169.7 2289.35   179.2 2295.15   183.9 2297.75   188.5 2298.96   193.4 2299.88
   197.2 2300.88   211.7 2305.19   221.7 2307.83   229.1 2310.31   234.5 2312.41
#Mann= 4 ,-1,0
       0     .06       0      30      .1       0  154.67    .045       0
   165.9      .1       0
#XS Ineff= 2 , 0
          120.77 2298.99
Permanent Ineff=
       F       F
Bank Sta=154.67,165.9
XS Rating Curve= 0 ,0
Exp/Cntr(USF)=0,0
Exp/Cntr=0.3,0.1

Type RM Length L Ch R = 1 ,213     ,50.9,49.7,48.7
XS GIS Cut Line= 2
 2263660.3027541 487293.629656032263524.88067167487212.004118633
#Sta/Elev= 30
       0 2308.25     9.5 2308.23    14.2 2307.69    18.8 2306.35    20.8  2305.1
    23.5 2303.65    29.6 2299.44    32.8 2297.08    37.5 2293.92    42.2 2291.48
    46.9 2289.92      50 2289.15    56.2 2287.23    70.2 2284.7179.041822283.744
    84.2 2283.3489.222252283.859    93.7 2284.24    96.6 2285.55    98.2 2286.54
   105.3 2292.85   108.2 2295.04   112.2  2296.2   126.3 2297.45   131.6 2298.83
   134.5 2300.31   140.3 2304.13   148.1 2308.58   154.3 2312.42   158.1 2314.53
#Mann= 4 ,-1,0
       0     .06       0      40      .1       079.04182    .045       0
89.22225      .1       0
Bank Sta=79.04182,89.22225
XS Rating Curve= 0 ,0
Exp/Cntr(USF)=0,0
Exp/Cntr=0.3,0.1

Type RM Length L Ch R = 1 ,163     ,75.8,81.3,86
XS GIS Cut Line= 2
2263670.40728217487234.2550149552263544.95521815487176.009413806
#Sta/Elev= 30
       0 2304.56     2.5 2304.91     6.9 2305.11    11.3 2304.61    20.6 2302.04
    24.5 2300.11    28.9 2297.23    38.6 2289.84    41.6 2287.82    44.7 2286.29
    53.7 2282.46    55.4 2281.93    59.7 2281.78    64.2  2282.2    65.7 2282.49
    68.8 2283.19    71.8 2284.75    77.8 2288.86    81.8 2292.02    86.3 2294.47
      88 2294.99    92.8 2296.06    95.9 2297.05   107.9 2302.46   112.7 2306.12
   116.9 2309.57   121.5 2312.59     129  2316.8     132 2318.35   138.3 2321.03
#Mann= 4 ,-1,0
       0     .06       0      40      .1       0    53.7    .045       0
    65.7      .1       0
Bank Sta=53.7,65.7
XS Rating Curve= 0 ,0
Exp/Cntr(USF)=0,0
Exp/Cntr=0.3,0.1

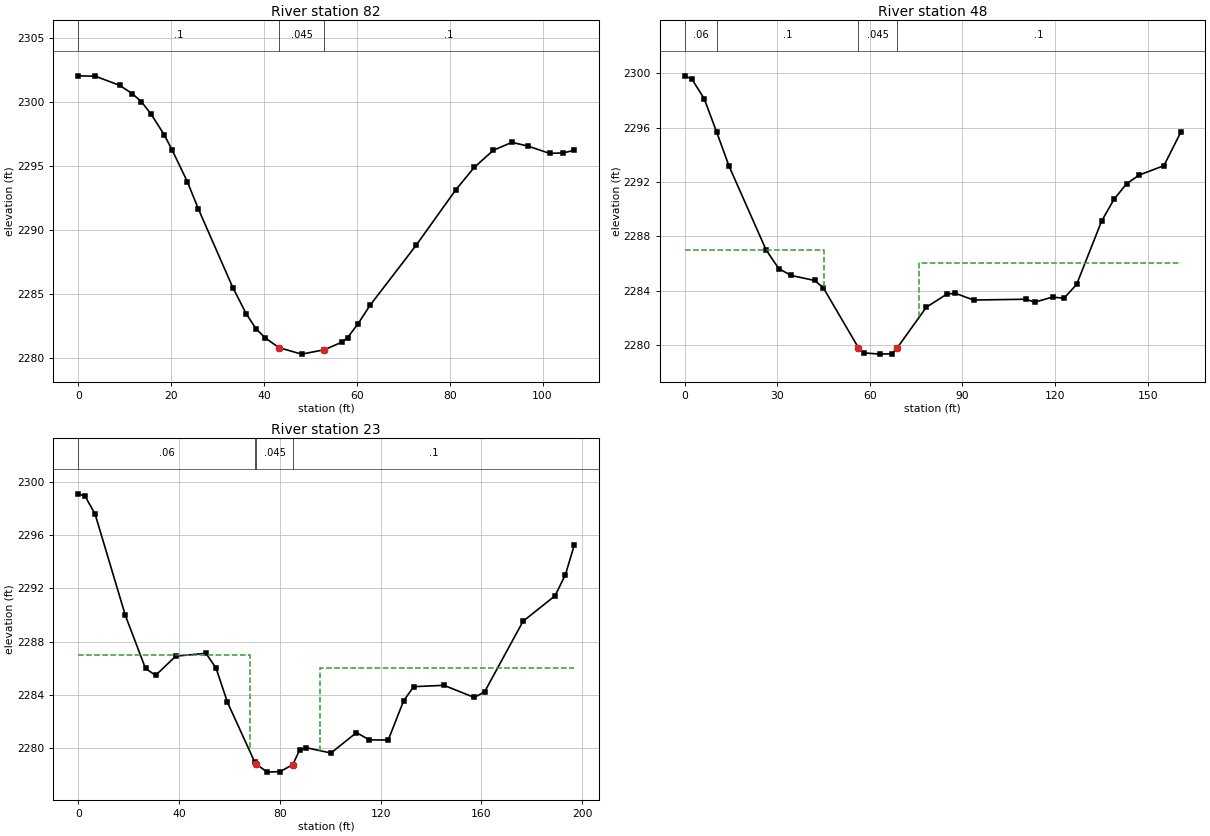
Type RM Length L Ch R = 1 ,82      ,36.3,33.7,29.8
XS GIS Cut Line= 3
2263705.35464286487200.2037404372263665.92685131487145.542483974
2263626.94710285487139.717923859
#Sta/Elev= 30
       0 2302.05     3.7 2302.02     8.9 2301.31    11.6 2300.67    13.6 2300.03
    15.7 2299.06    18.5 2297.46    20.2 2296.28    23.5 2293.79    25.9 2291.64
    33.3 2285.52    36.2 2283.47    38.3  2282.3    40.3 2281.59    43.2 2280.84
    48.1 2280.33      53 2280.67    56.7 2281.25      58 2281.61    60.3 2282.72
    62.9 2284.17    72.8 2288.84    81.3 2293.15    85.3 2294.91    89.4 2296.24
    93.4 2296.86    96.9 2296.56   101.5    2296   104.4 2296.03   106.8 2296.24
#Mann= 3 ,-1,0
       0      .1       0    43.2    .045       0      53      .1       0
Bank Sta=43.2,53
XS Rating Curve= 0 ,0
Exp/Cntr(USF)=0,0
Exp/Cntr=0.5,0.3

Type RM Length L Ch R = 1 ,48      ,25.5,25.3,25.4
XS GIS Cut Line= 4
2263730.22105046487195.4747859362263726.41266789487160.327905804
2263658.31011885487108.8029509412263618.88232731487115.075554142
#Sta/Elev= 30
       0 2299.81     2.3 2299.58     6.3 2298.14    10.4 2295.65    14.4 2293.15
    26.4 2286.99    30.5 2285.62    34.5 2285.12    42.1 2284.75    44.9 2284.22
    56.3  2279.8    58.2 2279.42    63.2 2279.33    67.1 2279.36   68.84 2279.78
    78.3 2282.78    84.9 2283.74    87.7 2283.81    93.6 2283.31   110.6 2283.37
   113.4 2283.15   119.2 2283.53   122.9 2283.44     127 2284.46   135.1 2289.12
   139.1 2290.72   143.2 2291.87   147.2  2292.5   155.3  2293.2   160.7 2295.64
#Mann= 4 ,-1,0
       0     .06       0    10.4      .1       0    56.3    .045       0
   68.84      .1       0
#XS Ineff= 2 , 0
              45    2287      76            2286
Permanent Ineff=
       F       F
Bank Sta=56.3,68.84
XS Rating Curve= 0 ,0
Exp/Cntr(USF)=0,0
Exp/Cntr=0.5,0.3

Type RM Length L Ch R = 1 ,23      ,4.3,4.3,4.3
XS GIS Cut Line= 4
2263738.82763361487195.8818276722263736.70747744487136.729470337
2263686.24776043487097.7185966832263612.67834109 487103.44301836
#Sta/Elev= 30
       0 2299.13     2.7 2298.96     6.7  2297.6    18.7 2289.97    26.7 2285.97
    30.7 2285.45    38.7  2286.9    50.7 2287.11    54.7 2285.99    59.2 2283.43
      70 2278.93    70.7 2278.75      75 2278.16    80.1  2278.2    85.1 2278.72
    87.8  2279.8    90.2 2280.01   100.3  2279.6   110.4 2281.14   115.5 2280.59
     123 2280.58   129.1 2283.53   133.1  2284.6   145.1  2284.7   157.1 2283.79
   161.2  2284.2   176.5 2289.53   189.2 2291.45   193.3 2293.04196.7633 2295.24
#Mann= 4 ,-1,0
       0     .06       0      70      .1       0    70.7    .045       0
    85.1      .1       0
#XS Ineff= 2 , 0
              68    2287      96            2286
Permanent Ineff=
       F       F
Bank Sta=70.7,85.1
XS Rating Curve= 0 ,0
Exp/Cntr(USF)=0,0
Exp/Cntr=0.5,0.3