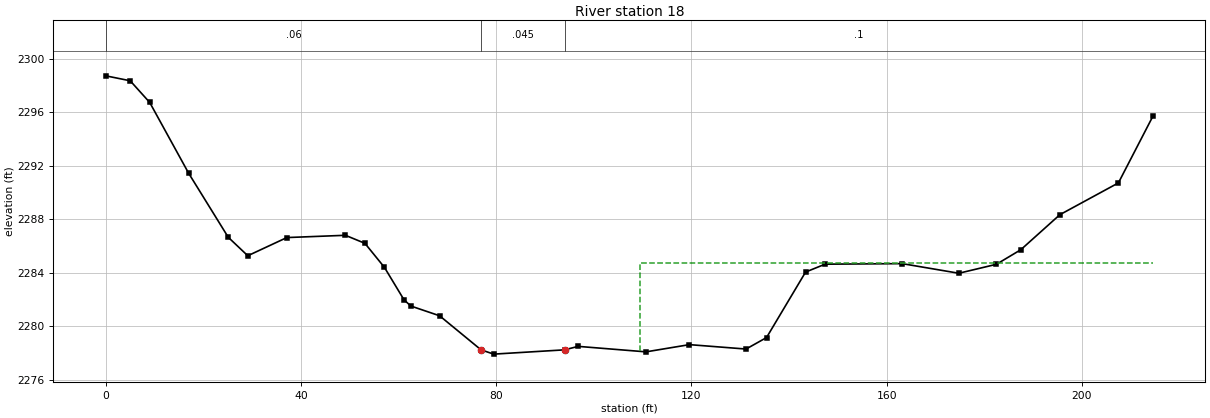
HEC-RAS study GLADERN.prj: GLADERN

--- GLADERN.g01 (geometry) --- (continued)

Type RM Length L Ch R = 1 ,18      ,,,
XS GIS Cut Line= 4
2263743.97559063487198.2168762552263741.87010823487135.801623415
2263687.34879458487092.2133561322263605.07887141487095.452309227
#Sta/Elev= 30
       0 2298.73       5 2298.36       9 2296.74      17 2291.43    25.1 2286.65
    29.1 2285.27    37.1 2286.63    49.1  2286.8    53.1  2286.2    57.1  2284.4
    61.1 2281.98    62.5 2281.51    68.4 2280.78    76.9 2278.23    79.5 2277.91
      94 2278.23    96.8 2278.49   110.7 2278.08   119.6 2278.62   131.2 2278.29
   135.4 2279.15   143.4 2284.05   147.4 2284.64   163.2 2284.68   174.8 2283.96
   182.5 2284.63   187.5 2285.72   195.5 2288.34   207.5 2290.72   214.6 2295.73
#Mann= 3 ,-1,0
       0     .06       0    76.9    .045       0      94      .1       0
#XS Ineff= 2 , 0
                           109.5         2284.71
Permanent Ineff=
       F       F
Bank Sta=76.9,94
XS Rating Curve= 0 ,0
Exp/Cntr(USF)=0,0
Exp/Cntr=0.3,0.1
LCMann Table=0

Chan Stop Cuts=-1
Use User Specified Reach Order=0
Composite Channel Slope=5